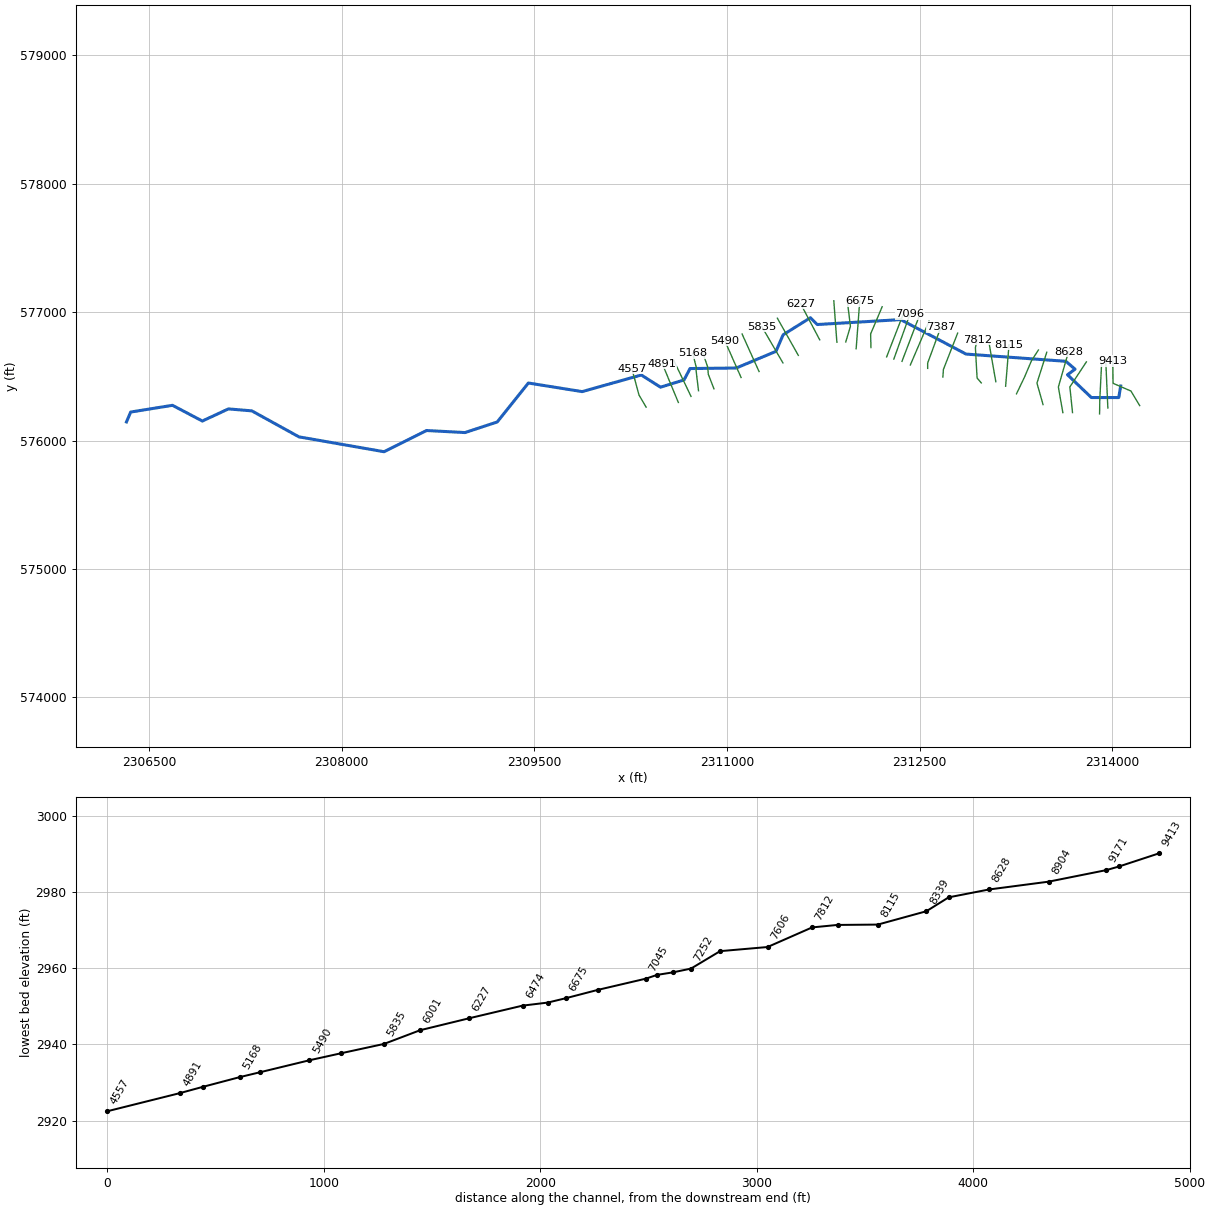
--- MNTNLCKCKT1.prj (project) ---

Proj Title=MNTNLCKCKT1
Current Plan=p01
Default Exp/Contr=0,0
English Units
Geom File=g01
Flow File=f01
Plan File=p01
Background Map Layer=Inundation Boundary (01pct Value_0)
BEGIN DESCRIPTION:
----------MODEL BY WOOD PLC 2021----------
Stream Name: Mountain Lick Creek Tributary 1
Flood Zone: Enhanced Approximate
Pocahontas County, WV
HEC-RAS Version: RAS 6.1
Vertical Datum: NAVD88
Projection: NAD 1983 StatePlane West Virginia S FIPS 4702 (US Feet)
Terrain: 1-meter LIDAR (FEMA Region III 3DEP collected 2016-2018)
Land Use: 2019 NLCD
Hydrologic Method:
WV SIR2010-5033 regression equations
Model Notes:
coincident peak / KWSEL tie in with MNTNLCKCK XS 5933
END DESCRIPTION:
DSS Export Rating Curves= 0
DSS Export Rating Curve Sorted= 0
DSS Export Volume Flow Curves= 0
DXF OffsetX= 0
DXF OffsetY= 0
DXF ScaleX= 0
DXF ScaleY= 0

--- MNTNLCKCKT1.p01 (plan) ---

Plan Title=Floodplain
Program Version=6.10
Short Identifier=Floodplain
Geom File=g01
Flow File=f01
Subcritical Flow
K Sum by GR= 0
Std Step Tol= 0.01
Critical Tol= 0.01
Num of Std Step Trials= 20
Max Error Tol= 0.3
Flow Tol Ratio= 0.001
Split Flow NTrial= 30
Split Flow Tol= 0.02
Split Flow Ratio= 0.02
Log Output Level= 0
Friction Slope Method= 1
Unsteady Friction Slope Method= 2
Unsteady Bridges Friction Slope Method= 1
Parabolic Critical Depth
Global Vel Dist= 0 , 0 , 0
Global Log Level= 0
CheckData=True
Encroach Param=-1 ,0,0, 0
Mapping Interval=1HOUR
Computation Time Step Use Courant=        0
Computation Time Step Use Time Series=    0
Computation Time Step Count To Double=0
Computation Time Step Max Doubling=0
Computation Time Step Max Halving=0
Computation Time Step Residence Courant=0
Run HTab= 0
Run UNet= 0
Run Sediment= 0
Run PostProcess= 0
Run WQNet= 0
Run RASMapper=-1
UNET Theta= 0
UNET Theta Warmup= 0
UNET ZTol= 0
UNET ZSATol= 0
UNET MxIter= 0
UNET Max Iter WO Improvement= 0
UNET MaxInSteps= 0
UNET DtIC= 0
UNET DtMin= 0
UNET MaxCRTS= 0
UNET WFStab= 0
UNET SFStab= 0
UNET WFX= 1
UNET SFX= 1
UNET Gravity=32.174
UNET 1D Methodology=Finite Difference
UNET DSS MLevel= 1
UNET Pardiso=0
UNET DZMax Abort= 0
UNET Use Existing IB Tables= 0
UNET Froude Reduction=False
UNET Froude Limit= 0
UNET Froude Power= 0
UNET D1 Cores= 0
UNET WindReference=Eulerian
UNET WindDragFormulation=Hsu (1988)
UNET D2 Coriolis=0
UNET D2 Cores= 0
UNET D2 Theta= 1
UNET D2 Theta Warmup= 1
UNET D2 Z Tol= 0.01
UNET D2 Volume Tol= 0.01
UNET D2 Max Iterations= 20
UNET D2 Equation= 0
UNET D2 RampUpFraction=0.1
UNET D2 TimeSlices= 1
UNET D2 Turbulence Formulation=Non-Conservative (original)
UNET D2 Eddy Viscosity=0.3
UNET D2 Transverse Eddy Viscosity=0.1
UNET D2 Smagorinsky Mixing=0
UNET D2 BCVolumeCheck=0
UNET D2 Cores=0
UNET D2 SolverType=PARDISO (Direct)
UNET D2 Minimum Iterations= 2147483647
UNET D2 Maximum Iterations= 2147483647
UNET D2 Restart Number= 10
UNET D2 Relaxation Coeff=1.3
UNET D2 SOR Precondition Iterations= 10
UNET D2 ILUT Maximum Fill= 8
UNET D2 ILUT Tolerance=1E-08
UNET D1D2 MaxIter= 0
UNET D1D2 ZTol=0.01
UNET D1D2 QTol=0.1
UNET D1D2 MinQTol=1
Write IC File= 0
Write IC File at Fixed DateTime=0
Write IC File at Sim End=0
Echo Input=False
Echo Parameters=False
Echo Output=False
Write Detailed= 0
HDF Write Warmup=0
HDF Write Time Slices=0
HDF Flush=0
HDF Compression= 1
HDF Chunk Size= 1
HDF Spatial Parts= 1
HDF Use Max Rows=0
HDF Fixed Rows= 1
Calibration Method= 0
Calibration Iterations= 20
Calibration Max Change=0.05
Calibration Tolerance=0.2
Calibration Maximum=1.5
Calibration Minimum=0.5
Calibration Optimization Method= 1
WQ AD Non Conservative
WQ ULTIMATE=-1
WQ Max Comp Step=1HOUR
WQ Output Interval=15MIN
WQ Output Selected Increments= 0
WQ Output face flow=0
WQ Output face velocity=0
WQ Output face area=0
WQ Output face dispersion=0
WQ Output cell volume=0
WQ Output cell surface area=0
WQ Output cell continuity=0
WQ Output cumulative cell continuity=0
WQ Output face conc=0
WQ Output face dconc_dx=0
WQ Output face courant=0
WQ Output face peclet=0
WQ Output face adv mass=0
WQ Output face disp mass=0
WQ Output cell mass=0
WQ Output cell source sink temp=0
WQ Output nsm pathways=0
WQ Output nsm derived pathways=0
WQ Create Restart=0
WQ Fixed Restart=0
WQ System Summary=0
WQ Write To DSS=0
Sorting and Armoring Iterations= 10
XS Update Threshold= 0.02
Bed Roughness Predictor= 0
Hydraulics Update Threshold= 0.02
Energy Slope Method= 1
Volume Change Method= 1
Sediment Retention Method= 0
Sediment TS Multiplier= 1
Warm Up Method= 0
XS Weighting Method= 0
Number of US Weighted Cross Sections= 1
Number of DS Weighted Cross Sections= 1
Upstream XS Weight=0
Main XS Weight=1
Downstream XS Weight=0
Number of DS XS's Weighted with US Boundary= 1
Upstream Boundary Weight= 1
Weight of XSs Associated with US Boundary= 0
Number of US XS's Weighted with DS Boundary= 1
Downstream Boundary Weight= 0.5
Weight of XSs Associated with DS Boundary= 0.5
Percentile Method= 0
Sediment Output Level= 3
Mass or Volume Output= 0
Output Increment Type= 1
Profile and TS Output Increment= 1
Transport Output Increment 1
XS Output Flag= 0
XS Output Increment= 10
Read HDF5 Sediment Hotstart= 0
Sediment Hotstart Type= 0
Write Gradation File= 0
Read Gradation Hotstart= 0
Write HDF5 File= 1
Write Binary Output= 1
Write DSS Sediment File= 0
DSS Sediment Output Type= 1
SV Curve= 0
Specific Gage Flag= 0
Subcell Erosion Methods= 0
Subcell Deposition Methods= 0
Advection Scheme= 1
Matrix Solver= 0
Implicit Weighting Factor= 1
Maximum Outer Loop Convergence Iterations= 5
Convergence Maximum Absolute= 0.001
Convergence RMSE= 0.0001
Grain Fractions Max Abs Error= 0.001
Max Subgrid Regions= 1
Max Subgrid Length Scale= 3.402823E+38
Initial Layer Thickness= 3.402823E+38
Min Layer Thickness= 3.402823E+38
Max Layer Thickness= 3.402823E+38
Number of Layers= 5

--- MNTNLCKCKT1.f01 (steady flow) ---

Flow Title=Flow
Program Version=6.10
Number of Profiles= 6
Profile Names=01pct,10pct,04pct,02pct,0_2pct,01plus
River Rch & RM=MNTNLCKCKT1,Main            ,9413
     581     307     408     492     811     859
River Rch & RM=MNTNLCKCKT1,Main            ,6675
     649     345     457     550     905     960
River Rch & RM=MNTNLCKCKT1,Main            ,4557
     723     385     510     613    1010    1070
River Rch & RM=MNTNLCKCKT1,Main            ,0
    1530     840    1100    1310    2100    2260
Boundary for River Rch & Prof#=MNTNLCKCKT1,Main            , 1
Up Type= 0
Dn Type= 1
Dn Known WS=2829.9
Boundary for River Rch & Prof#=MNTNLCKCKT1,Main            , 2
Up Type= 0
Dn Type= 1
Dn Known WS=2828.6
Boundary for River Rch & Prof#=MNTNLCKCKT1,Main            , 3
Up Type= 0
Dn Type= 1
Dn Known WS=2829.1
Boundary for River Rch & Prof#=MNTNLCKCKT1,Main            , 4
Up Type= 0
Dn Type= 1
Dn Known WS=2829.5
Boundary for River Rch & Prof#=MNTNLCKCKT1,Main            , 5
Up Type= 0
Dn Type= 1
Dn Known WS=2830.7
Boundary for River Rch & Prof#=MNTNLCKCKT1,Main            , 6
Up Type= 0
Dn Type= 1
Dn Known WS=2830.9
DSS Import GetInterval= 0
DSS Import GetPeak= 0
DSS Import FillOption= 0

--- MNTNLCKCKT1.g01 (geometry) ---

Geom Title=Geometry
Program Version=6.10

River Reach=MNTNLCKCKT1     ,Main
Reach XY= 30
 2314065.4810313576424.7438658182314050.50041822576334.687615484
2313837.25412555576334.9999508112313651.48776481 576512.40543589
2313710.07065289576556.0123040682313639.09047988 576617.06205073
2312861.54183814  576673.4799169 2312352.4588668576941.894078225
2311703.09107105576903.5224358142311649.88284414576956.351070315
2311437.75006631576823.7591438892311381.35057281576694.392604724
2311072.74193805576564.953887224 2310712.7259258576560.729158148
2310665.81132147576471.9560417232310482.89797339576415.610025808
2310333.44387597  576510.56291992309872.61901022576381.180304646
2309454.33802263576448.1201313882309211.67676255576144.811026722
2308961.03618772576062.3938687292308661.60994931576078.242918387
2308330.82813056575913.0995478932307667.95412822576028.976940811
2307301.15893005576231.2898563892307118.83810046576246.572962314
2306916.02518588576152.1207233972306683.48300006576274.519100636
2306358.09126239576222.1071319732306325.13201071576144.876971483

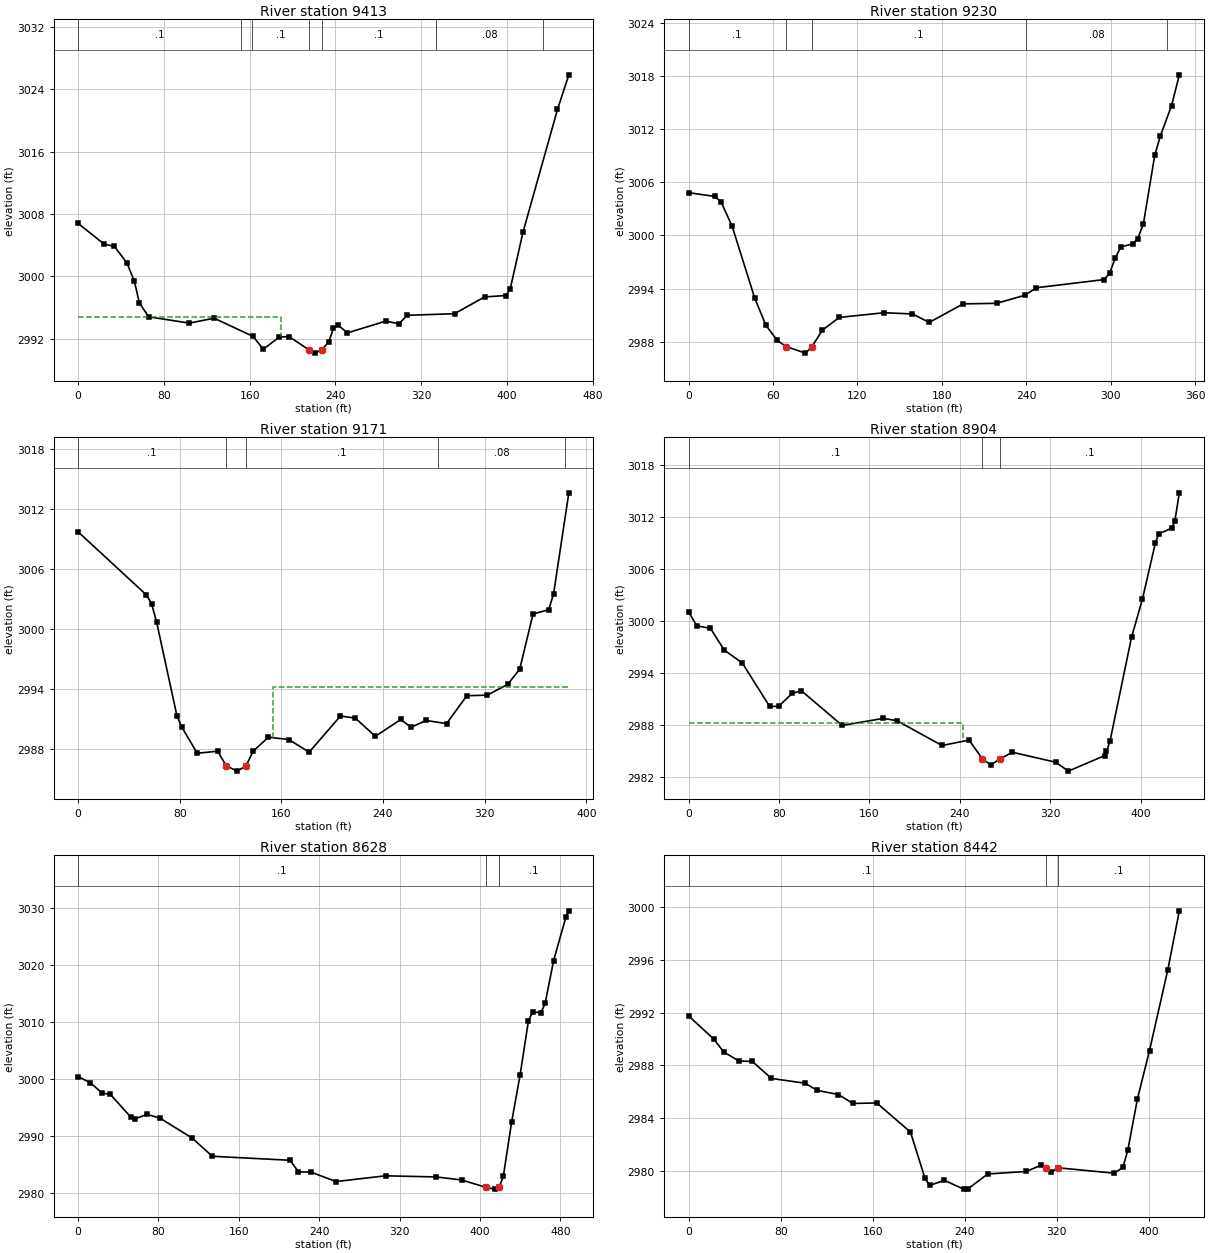
Type RM Length L Ch R = 1 ,9413    ,257.7,183.7,257.7
XS GIS Cut Line= 4
 2314213.6025847576272.2055683692314145.45438257576385.478931378
2314006.39521334576445.7992994852314003.63244839576619.853491426
#Sta/Elev= 30
       0 3006.78    24.5 3004.11    33.8 3003.84    45.5 3001.73    52.5 2999.36
    57.2 2996.56    65.9  2994.8   103.8 2993.99   126.9 2994.62   163.3 2992.28
   172.8 2990.64   187.7  2992.2   196.8 2992.27     215 2990.59   220.8 2990.14
   227.2 2990.56   233.9 2991.59   238.2 2993.32   242.6 2993.72   251.3 2992.74
   287.2 2994.25   299.2 2993.91   307.2 2994.99   351.2  2995.2   379.2 2997.35
   399.2 2997.53   403.2 2998.43     415 3005.64   447.2  3021.4   457.8 3025.84
#Mann= 7 ,-1,0
       0      .1       0  152.19     .08       0  162.19      .1       0
     215    .045       0   227.2      .1       0  333.77     .08       0
  433.77      .1       0
#XS Ineff= 2 , 0
          189.67 2994.83
Permanent Ineff=
       F       F
Bank Sta=215,227.2
XS Rating Curve= 0 ,0
Exp/Cntr(USF)=0,0
Exp/Cntr=0.3,0.1

Type RM Length L Ch R = 1 ,9230    ,60.2,58.6,56.9
XS GIS Cut Line= 2
2313965.51838461 576254.197304422313950.10470929576602.680398603
#Sta/Elev= 30
       0 3004.82    18.5  3004.4      23 3003.81      31 3001.02      47 2992.93
      55 2989.84      63 2988.16    69.22987.457    83.1 2986.71    87.62987.411
    95.1  2989.3   107.1 2990.74   139.1 2991.27   159.1 2991.13   171.1 2990.18
   195.2 2992.27   218.9 2992.33   239.2 2993.25   247.2 2994.09   295.3 2995.01
   299.3 2995.72   303.2 2997.44   307.3 2998.69   315.9 2999.06   319.3 2999.64
   323.3 3001.33   331.3 3009.02   335.3 3011.22   343.3 3014.65   348.8 3018.12
#Mann= 5 ,-1,0
       0      .1       0    69.2    .045       0    87.6      .1       0
     240     .08       0     340      .1       0
Bank Sta=69.2,87.6
XS Rating Curve= 0 ,0
Exp/Cntr(USF)=0,0
Exp/Cntr=0.3,0.1

Type RM Length L Ch R = 1 ,9171    ,276.2,267.2,257.6
XS GIS Cut Line= 3
2313901.08821146576207.390809204 2313902.9175591576320.612203006
2313916.59671947576593.298161452
#Sta/Elev= 30
       0 3009.71    53.8 3003.39    57.8 3002.53    61.8 3000.69    77.8  2991.3
    81.8 2990.13    93.8 2987.55   109.8 2987.75   116.7 2986.29   125.2 2985.76
   132.12986.268   137.8 2987.75   149.8 2989.16   165.9 2988.92   181.9 2987.66
   206.5 2991.27   218.2 2991.07     234 2989.24     254 2990.93     262 2990.15
     274 2990.83     290 2990.51     306 2993.31   322.1 2993.36   338.1 2994.44
   347.6 2995.95   358.1 3001.48   370.5 3001.92   374.3 3003.52   386.3 3013.61
#Mann= 5 ,-1,0
       0      .1       0   116.7    .045       0   132.1      .1       0
  283.24     .08       0  383.24      .1       0
#XS Ineff= 2 , 0
                          153.49         2994.15
Permanent Ineff=
       F       F
Bank Sta=116.7,132.1
XS Rating Curve= 0 ,0
Exp/Cntr(USF)=0,0
Exp/Cntr=0.3,0.1

Type RM Length L Ch R = 1 ,8904    ,262.5,275.3,246
XS GIS Cut Line= 3
2313690.51908723 576217.871190992313669.79835009576417.711189145
2313798.26692034576612.486118222
#Sta/Elev= 30
       0 3001.06     7.3 2999.44    19.4 2999.15    31.5 2996.66    47.6 2995.16
    71.7 2990.17    79.7 2990.18    91.8 2991.68    99.8 2991.97     136 2987.98
   172.2 2988.79   184.3 2988.53   224.2 2985.67   248.2 2986.29     260 2984.13
   267.4 2983.43   275.1 2984.09   286.5 2984.89   324.9 2983.74     336 2982.72
     368  2984.5   369.7    2985   372.8 2986.13   391.9 2998.12   401.5 3002.49
     413 3008.98   415.9 3010.03   427.5 3010.68   430.3 3011.55   434.2 3014.75
#Mann= 3 ,-1,0
       0      .1       0     260    .045       0   275.1      .1       0
#XS Ineff= 2 , 0
          242.54 2988.31
Permanent Ineff=
       F       F
Bank Sta=260,275.1
XS Rating Curve= 0 ,0
Exp/Cntr(USF)=0,0
Exp/Cntr=0.3,0.1

Type RM Length L Ch R = 1 ,8628    ,190.2,186,187.5
XS GIS Cut Line= 3
2313615.19013641576217.5029597682313580.25725264576416.988111814
2313659.31588432576691.854749887
#Sta/Elev= 30
       0 3000.44    11.9 2999.39      24 2997.55    32.2  2997.3    52.5 2993.32
    56.5 2993.01    68.7 2993.81    81.8 2993.11   113.4 2989.66   133.6 2986.44
     211 2985.74   219.4 2983.71   231.7 2983.66   256.8    2982     306 2983.01
   356.7 2982.81   381.7 2982.28   406.3 2980.97     415 2980.67   419.1 2980.99
   423.3 2982.95   431.6 2992.51     440 3000.76   448.3 3010.26   452.4 3011.76
   460.8 3011.69   464.9  3013.3   473.3  3020.8   485.7 3028.55   488.5 3029.56
#Mann= 3 ,-1,0
       0      .1       0   406.3    .045       0   419.1      .1       0
Bank Sta=406.3,419.1
XS Rating Curve= 0 ,0
Exp/Cntr(USF)=0,0
Exp/Cntr=0.3,0.1

Type RM Length L Ch R = 1 ,8442    ,106.5,103.1,99.9
XS GIS Cut Line= 3
2313461.08328358576279.8753465882313413.61715971576447.490096502
2313490.00795281576687.787348591
#Sta/Elev= 30
       0 2991.76    22.1 2989.98    30.5 2989.02    43.9 2988.33    55.4  2988.3
      72 2987.01   101.1 2986.65   111.9  2986.1   130.2 2985.79   142.7 2985.11
   163.5 2985.15   192.8 2982.94   205.4 2979.44   209.4 2978.89   222.3 2979.28
   238.9 2978.61   243.1 2978.65   259.9 2979.76   293.5 2979.95   306.1 2980.42
   310.3 2980.22   314.7 2979.88   320.9 2980.23   369.8 2979.82   377.4 2980.26
   381.6 2981.55     390 2985.46   400.5 2989.13   416.4 2995.26   426.4 2999.73
#Mann= 3 ,0,0
       0      .1       0   310.3    .045       0   320.9      .1       0
Bank Sta=310.3,320.9
XS Rating Curve= 0 ,0
Exp/Cntr(USF)=0,0
Exp/Cntr=0.3,0.1

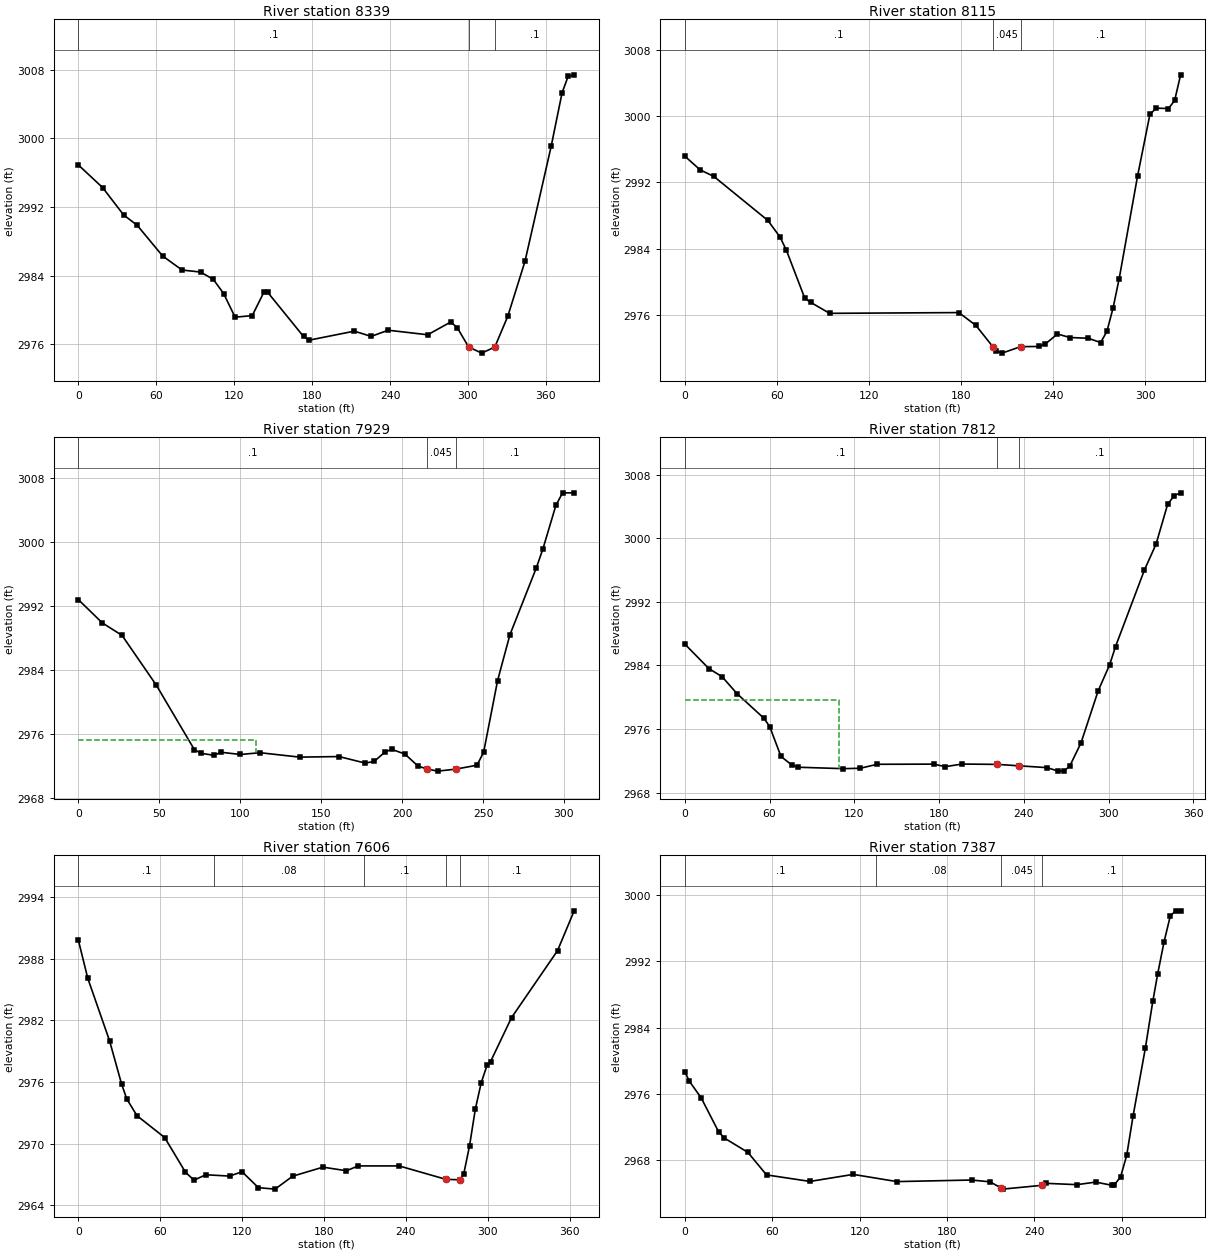
Type RM Length L Ch R = 1 ,8339    ,212.5,224.2,241.6
XS GIS Cut Line= 4
2313254.46268572576364.2977334172313317.08535796576495.068607786
2313370.95927451576621.6953347272313424.83319106576705.038744096
#Sta/Elev= 30
       0 2996.89    18.7 2994.25    34.9 2991.06    45.3 2989.86    64.9 2986.28
    79.9 2984.64    94.1 2984.41   103.9 2983.56   111.9  2981.9   120.7 2979.15
   133.9 2979.33   142.9 2982.06   145.9 2982.03   173.4  2976.9   177.7 2976.47
   212.5 2977.52   225.5 2976.91   238.6 2977.63     269  2977.1   286.8 2978.59
   291.8 2977.92   300.5 2975.68   310.6 2974.96   320.7 2975.67   330.7 2979.26
   343.9 2985.64   364.1 2999.06   372.5  3005.3   377.2 3007.23   381.8 3007.39
#Mann= 3 ,-1,0
       0      .1       0   300.5    .045       0   320.7      .1       0
Bank Sta=300.5,320.7
XS Rating Curve= 0 ,0
Exp/Cntr(USF)=0,0
Exp/Cntr=0.3,0.1

Type RM Length L Ch R = 1 ,8115    ,162,185.9,144.9
XS GIS Cut Line= 2
2313169.73789388576423.2367190482313195.98416092576745.098835892
#Sta/Elev= 30
       0 2995.17      10 2993.52    18.9 2992.73    54.1 2987.43    62.1 2985.41
    66.2 2983.82    78.2 2978.04      82 2977.57    94.3 2976.25   178.5 2976.34
   189.6 2974.79   200.7 2972.21   202.6 2971.75   206.6 2971.46   218.7 2972.24
   230.7 2972.26   234.7 2972.55   242.7 2973.76   250.8 2973.34   262.8 2973.25
   270.8 2972.73   274.9 2974.08   278.9 2976.89   282.9 2980.44   294.9 2992.82
   302.9  3000.2     307 3000.95     315  3000.9     319 3001.87   322.9 3004.96
#Mann= 3 ,-1,0
       0      .1       0   200.7    .045       0   218.7      .1       0
Bank Sta=200.7,218.7
XS Rating Curve= 0 ,0
Exp/Cntr(USF)=0,0
Exp/Cntr=0.3,0.1

Type RM Length L Ch R = 1 ,7929    ,119.9,117.3,115.8
XS GIS Cut Line= 3
2313093.41068329576458.5612162062313059.60538803576649.652458682
2313040.80886281576760.294043125
#Sta/Elev= 30
       0  2992.8    14.8 2989.89      27 2988.33    48.2  2982.1    71.7 2974.05
    75.8  2973.6    83.9 2973.34      88 2973.73   100.1 2973.45   112.3 2973.67
   136.7 2973.12   161.1 2973.19   177.3 2972.37   182.8 2972.59   189.5 2973.77
   193.6 2974.09   201.7 2973.51   209.8 2972.01   215.32971.642     222 2971.37
   233.12971.618   246.3 2972.11   250.4 2973.75     259 2982.69   266.6  2988.4
   282.8  2996.7   286.9 2999.07     295 3004.56   299.1 3006.13   306.3 3006.14
#Mann= 3 ,-1,0
       0      .1       0   215.3    .045       0   233.1      .1       0
#XS Ineff= 2 , 0
          109.98 2975.22
Permanent Ineff=
       F       F
Bank Sta=215.3,233.1
XS Rating Curve= 0 ,0
Exp/Cntr(USF)=0,0
Exp/Cntr=0.3,0.1

Type RM Length L Ch R = 1 ,7812    ,216.3,206.1,200.6
BEGIN DESCRIPTION:
banks placed per imagery
END DESCRIPTION:
XS GIS Cut Line= 4
2312980.03150826576448.9869550962312947.46174215576487.527844993
2312934.43383571576723.6586492922312948.54740103576786.084034337
#Sta/Elev= 30
       0 2986.69    17.1  2983.6    26.4 2982.59    36.9 2980.47    56.1 2977.35
    60.1 2976.32    68.1 2972.56    76.1 2971.45    80.2 2971.21   112.3 2971.03
   124.2 2971.08   136.2 2971.58   176.3  2971.6   184.3 2971.28   196.3 2971.61
   221.22971.567   236.52971.389   256.4 2971.16   264.4 2970.72   268.4 2970.77
   272.4 2971.31   280.5 2974.28   292.6  2980.8   300.8 2984.11   304.9 2986.37
   325.4 2996.01   333.6 2999.25   341.8 3004.25   346.5 3005.36     351  3005.7
#Mann= 3 ,-1,0
       0      .1       0   221.2    .045       0   236.5      .1       0
#XS Ineff= 2 , 0
          108.97 2979.66
Permanent Ineff=
       F       F
Bank Sta=221.2,236.5
XS Rating Curve= 0 ,0
Exp/Cntr(USF)=0,0
Exp/Cntr=0.3,0.1

Type RM Length L Ch R = 1 ,7606    ,174.9,219.1,180.5
XS GIS Cut Line= 3
2312681.25645996576494.2935394622312685.27512497576553.753036084
2312796.22862904576836.554952906
#Sta/Elev= 30
       0 2989.82     6.9 2986.11    22.9 2980.01    31.7  2975.8    35.5 2974.35
      43 2972.72    63.3 2970.59    78.5 2967.22    84.8 2966.44    93.4 2966.97
   110.8 2966.84     120 2967.26     132 2965.71   144.2 2965.57   157.1 2966.83
   179.3 2967.71   196.5 2967.36   205.1 2967.83   235.1 2967.83   269.5 2966.52
   279.7 2966.48   282.4    2967   286.7 2969.77     291 2973.39   295.3 2975.94
   299.6 2977.65   302.1 2977.98   317.5 2982.27   351.2 2988.79   363.4 2992.67
#Mann= 5 ,-1,0
       0      .1       0    99.6     .08       0   209.6      .1       0
   269.5    .045       0   279.7      .1       0
Bank Sta=269.5,279.7
XS Rating Curve= 0 ,0
Exp/Cntr(USF)=0,0
Exp/Cntr=0.3,0.1

Type RM Length L Ch R = 1 ,7387    ,139.5,134.5,131.2
XS GIS Cut Line= 3
2312562.71342541576562.0054912922312562.59567262576603.150514685
2312665.93101753576883.863999934
#Sta/Elev= 30
       0 2978.67     3.2 2977.51    11.2 2975.53    23.2 2971.42    27.2 2970.66
    43.3 2968.93    56.1 2966.21    85.9 2965.42   115.6 2966.27   145.6  2965.4
   196.8 2965.59   209.5 2965.37   217.3 2964.61   218.1 2964.49   245.12964.949
   247.9 2965.19   269.2 2965.03     282 2965.34   293.2 2964.95   294.8    2965
   299.1 2965.98   303.3 2968.57   307.6 2973.27   316.1 2981.54   321.2 2987.18
   324.6 2990.54   328.9 2994.35   333.2 2997.49   336.8 2998.12   340.3 2998.09
#Mann= 4 ,-1,0
       0      .1       0  131.15     .08       0   217.3    .045       0
   245.1      .1       0
Bank Sta=217.3,245.1
XS Rating Curve= 0 ,0
Exp/Cntr(USF)=0,0
Exp/Cntr=0.3,0.1

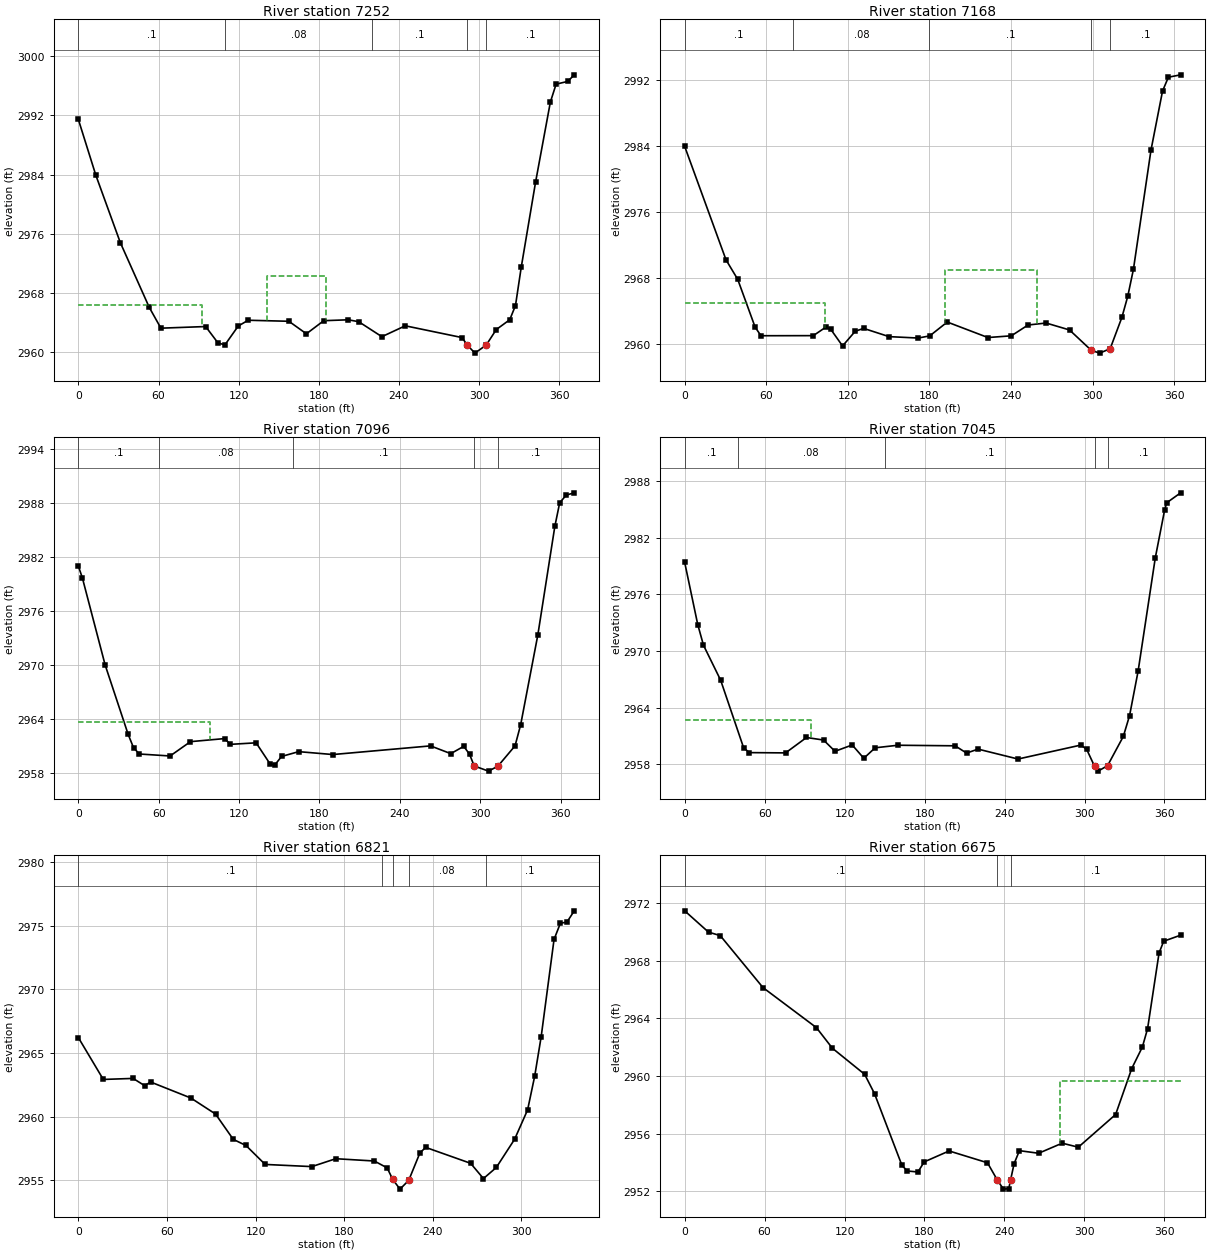
Type RM Length L Ch R = 1 ,7252    ,84.2,84.6,85.4
XS GIS Cut Line= 3
2312427.83232026576588.3406928972312536.01956242576840.550504339
2312573.60368553576929.709191485
#Sta/Elev= 30
       0 2991.47    13.1 2983.93    31.4 2974.84    53.1 2966.08    61.8 2963.28
    95.3  2963.5   104.5 2961.29   109.7 2961.02   119.7 2963.57   127.1 2964.35
   157.6 2964.21   170.7 2962.52   183.7 2964.29   201.9 2964.41   209.8 2964.16
   227.2 2962.13   244.7  2963.6   287.2 2962.01     2912961.024   296.8 2959.91
   305.3    2961   312.8 2963.09   322.9 2964.42   327.2 2966.34   331.5 2971.51
   342.2 2982.97   353.3 2993.81   357.6 2996.23   366.3  2996.6   371.2 2997.49
#Mann= 5 ,-1,0
       0      .1       0     110     .08       0     220      .1       0
     291    .045       0   305.3      .1       0
#XS Ineff= 2 ,-1
       0    92.5 2966.45  141.53  185.38 2970.37
Permanent Ineff=
       F       F
Bank Sta=291,305.3
XS Rating Curve= 0 ,0
Exp/Cntr(USF)=0,0
Exp/Cntr=0.3,0.1

Type RM Length L Ch R = 1 ,7168    ,72.6,72.1,72.6
XS GIS Cut Line= 2
2312362.83444048576616.7212505642312492.57067548 576957.61813585
#Sta/Elev= 30
       0 2983.98    30.4 2970.22      39 2967.86    51.8 2962.06    56.1 2961.02
    94.6 2961.03   103.7 2962.05   107.5 2961.78   116.1 2959.78   125.4 2961.56
   131.6 2961.91   150.3 2960.91   171.7 2960.74   180.2    2961   193.1 2962.68
     223  2960.8   240.2 2961.01   252.5 2962.32   265.8 2962.56     283 2961.72
     299 2959.25   305.2 2958.91   312.9 2959.45   321.5 2963.24   325.8 2965.78
     330 2969.08   342.9 2983.52   351.4 2990.69   355.7 2992.37   364.7 2992.66
#Mann= 5 ,-1,0
       0      .1       0      80     .08       0     180      .1       0
     299    .045       0   312.9      .1       0
#XS Ineff= 2 ,-1
       0  102.83 2964.96  191.36  259.14 2969.05
Permanent Ineff=
       F       F
Bank Sta=299,312.9
XS Rating Curve= 0 ,0
Exp/Cntr(USF)=0,0
Exp/Cntr=0.3,0.1

Type RM Length L Ch R = 1 ,7096    ,52.4,51,50.4
XS GIS Cut Line= 2
2312299.35806531576634.3867754222312424.42149933576982.858980205
#Sta/Elev= 30
       0    2981       3  2979.7      20 2970.04    37.2 2962.33    41.2 2960.86
    45.5 2960.16    68.5 2959.94    83.7 2961.53   109.2 2961.87   113.5 2961.23
   132.7  2961.4   143.2 2959.04   146.7 2958.95   151.7 2959.89   164.5 2960.42
     190  2960.1   262.9 2961.06     278  2960.2   287.7 2961.01     292 2960.14
   295.52958.833   306.2 2958.26   313.2 2958.81     326 2961.07   330.2 2963.42
     343 2973.37   355.7 2985.42   359.3 2988.02   364.2 2988.88   370.2 2989.13
#Mann= 5 ,-1,0
       0      .1       0      60     .08       0     160      .1       0
   295.5    .045       0   313.2      .1       0
#XS Ineff= 2 , 0
            98.4 2963.72
Permanent Ineff=
       F       F
Bank Sta=295.5,313.2
XS Rating Curve= 0 ,0
Exp/Cntr(USF)=0,0
Exp/Cntr=0.3,0.1

Type RM Length L Ch R = 1 ,7045    ,224.1,223.6,223.7
XS GIS Cut Line= 2
2312243.41196474 576652.005163852312378.03366466576998.873172923
#Sta/Elev= 30
       0 2979.38     9.8  2972.8    14.1 2970.61      27  2966.9    44.2 2959.76
    48.5 2959.24    75.7 2959.21    91.4 2960.84   104.2 2960.57   112.8 2959.38
   125.7 2960.05   134.4 2958.64   142.9 2959.75     160 2960.02   202.9 2959.96
   211.5 2959.19   220.1 2959.61   250.1 2958.56   297.3 2960.04   301.6 2959.59
   307.5  2957.8   310.2 2957.28   317.3 2957.86   329.1 2960.95   333.8 2963.16
   340.2 2967.86   353.1 2979.86   360.1 2984.92   361.7 2985.69   372.1 2986.74
#Mann= 5 ,-1,0
       0      .1       0      40     .08       0     150      .1       0
   307.5    .045       0   317.3      .1       0
#XS Ineff= 2 , 0
           94.46 2962.68
Permanent Ineff=
       F       F
Bank Sta=307.5,317.3
XS Rating Curve= 0 ,0
Exp/Cntr(USF)=0,0
Exp/Cntr=0.3,0.1

Type RM Length L Ch R = 1 ,6821    ,141.1,146,150.1
XS GIS Cut Line= 3
2312121.23927847576724.3076227292312118.72965181576830.115014081
2312208.52666984577041.800391249
#Sta/Elev= 30
       0 2966.22    16.9 2962.93    37.1 2963.01    44.9 2962.44    48.9 2962.73
    76.2 2961.47    92.9 2960.21   104.9 2958.22   113.5 2957.74   126.5 2956.25
   158.1 2956.08   174.3  2956.7   200.4 2956.52   209.1 2955.98   212.92955.067
   217.8 2954.31   223.7    2955   231.3 2957.16   235.2 2957.59   265.6 2956.34
   274.3 2955.14     283 2956.01   295.4 2958.23   304.2 2960.54     309 2963.19
   313.4  2966.3   322.1 2973.93   326.4 2975.21   330.8 2975.29   335.8 2976.18
#Mann= 5 ,-1,0
       0      .1       0  205.84     .08       0   212.9    .045       0
   223.7     .08       0  275.84      .1       0
Bank Sta=212.9,223.7
XS Rating Curve= 0 ,0
Exp/Cntr(USF)=0,0
Exp/Cntr=0.3,0.1

Type RM Length L Ch R = 1 ,6675    ,81.1,84.7,83.9
XS GIS Cut Line= 2
2312006.02746553576714.5410672232312033.88250311577085.752078191
#Sta/Elev= 30
       0 2971.47    17.9 2969.99    26.7 2969.75    58.8 2966.14    98.9 2963.36
   110.9 2961.93   135.1 2960.12   142.5 2958.78   163.1  2953.8   167.1 2953.41
   175.1 2953.34   179.8 2954.04   198.5  2954.8   227.3 2953.98   234.7 2952.78
   239.3 2952.15   243.3 2952.19   244.72952.803   247.3 2953.92   251.3 2954.82
   265.7 2954.64   283.4 2955.34   295.5 2955.06   323.5 2957.33   335.6 2960.52
   343.6 2962.02   347.5 2963.29   356.1 2968.54   359.6 2969.36   372.3 2969.78
#Mann= 3 ,-1,0
       0      .1       0   234.7    .045       0   244.7      .1       0
#XS Ineff= 1 ,-1
  281.92372.2546 2959.67
Permanent Ineff=
       F
Bank Sta=234.7,244.7
XS Rating Curve= 0 ,0
Exp/Cntr(USF)=0,0
Exp/Cntr=0.3,0.1

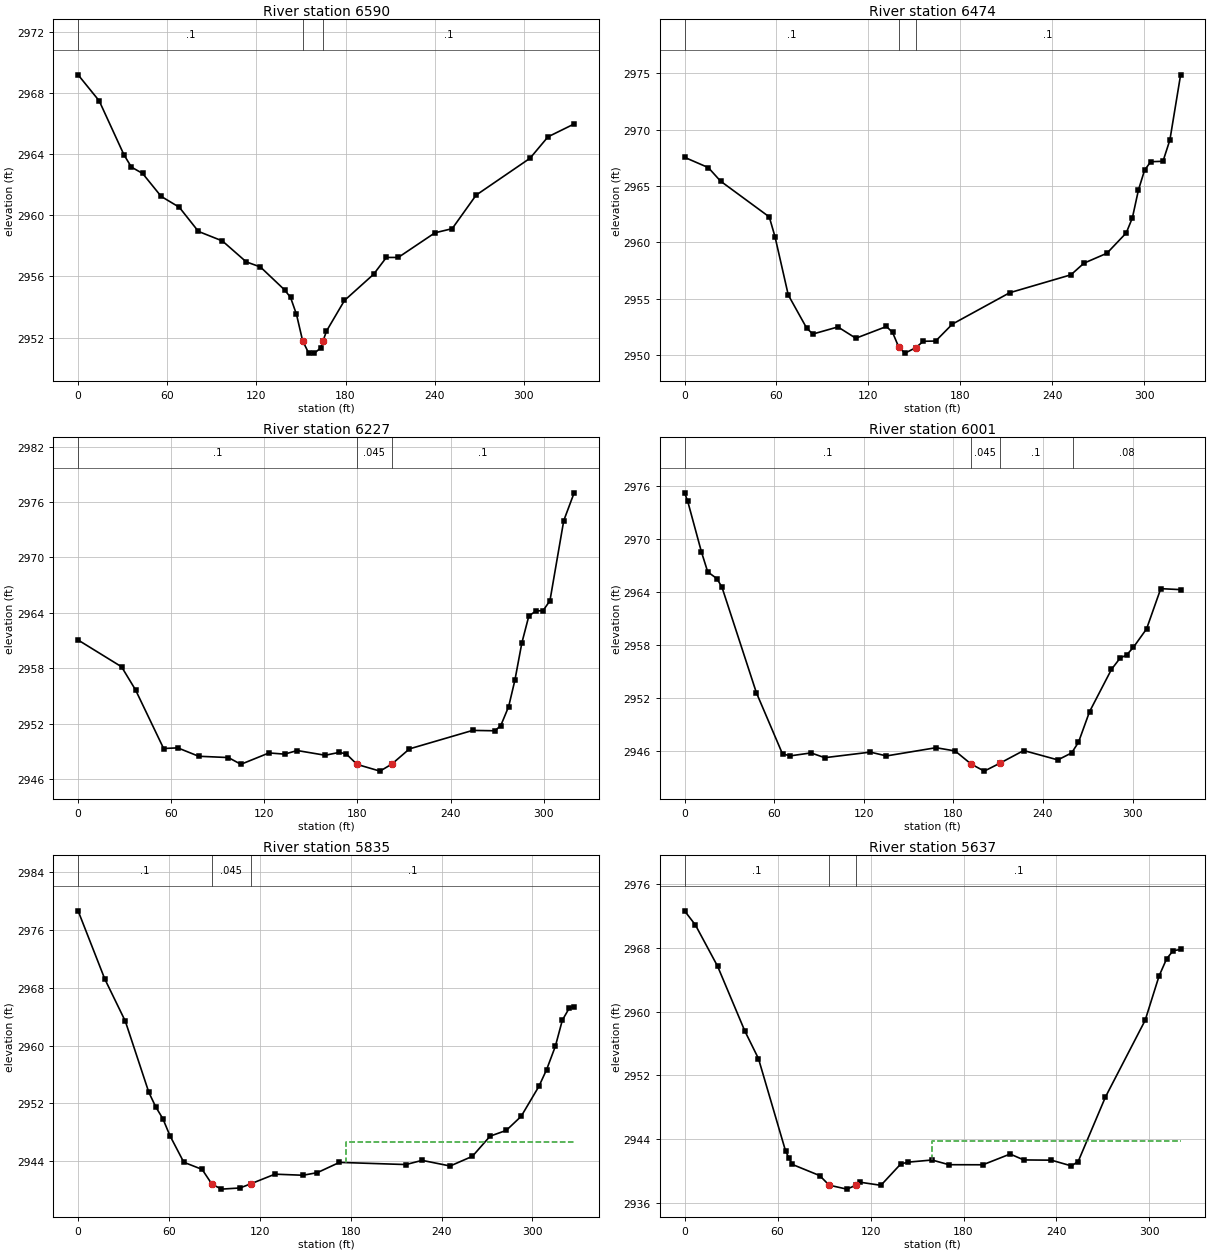
Type RM Length L Ch R = 1 ,6590    ,116.4,116,114.7
XS GIS Cut Line= 3
2311925.08192897 576767.577212482311961.42318005576889.950813074
2311936.20680175577094.648472248
#Sta/Elev= 30
       0 2969.17    14.2 2967.47    30.9 2963.94    35.9 2963.14    43.4 2962.73
    55.9 2961.23    68.1 2960.52      81 2958.94    97.1 2958.32   113.2 2956.95
   122.7 2956.62     139 2955.12     143 2954.63     147 2953.52   151.1 2951.81
   155.1 2951.01   159.1 2950.99   163.2 2951.32   164.92951.792   167.2 2952.43
   179.3 2954.43   198.9 2956.14   207.5 2957.24   215.5 2957.24   240.2 2958.85
   251.8 2959.12   267.9 2961.31   304.2 2963.72   316.3 2965.12   333.9 2965.96
#Mann= 3 ,-1,0
       0      .1       0   151.1    .045       0   164.9      .1       0
Bank Sta=151.1,164.9
XS Rating Curve= 0 ,0
Exp/Cntr(USF)=0,0
Exp/Cntr=0.3,0.1

Type RM Length L Ch R = 1 ,6474    ,234.7,247.8,255
XS GIS Cut Line= 2
2311855.95134471576765.7033811392311832.07559821577088.594428964
#Sta/Elev= 30
       0 2967.54    15.5 2966.63    23.5 2965.43    55.3 2962.26    59.1 2960.47
    67.7 2955.34    79.7 2952.41    83.7 2951.88   100.1 2952.51   111.8 2951.51
   131.8 2952.55   135.8 2952.02   139.9 2950.69   143.9 2950.19   150.82950.663
   155.9 2951.24   163.9 2951.26   174.8 2952.76   212.2 2955.54   252.2 2957.13
   260.7 2958.16   275.7 2959.04   288.3 2960.84   292.3 2962.17   296.3 2964.66
   300.3 2966.41   304.3 2967.15   312.3 2967.19   316.8 2969.08   323.8 2974.85
#Mann= 3 ,-1,0
       0      .1       0   139.9    .045       0   150.8      .1       0
Bank Sta=139.9,150.8
XS Rating Curve= 0 ,0
Exp/Cntr(USF)=0,0
Exp/Cntr=0.3,0.1

Type RM Length L Ch R = 1 ,6227    ,223.3,225.2,224.8
XS GIS Cut Line= 2
2311722.36085837576784.4628962422311572.85320771577066.992563089
#Sta/Elev= 30
       0 2961.06      28 2958.16      37 2955.66    55.1 2949.31    64.2 2949.38
    77.7 2948.47    96.8 2948.33   104.9  2947.6     123 2948.83     133  2948.7
   141.2 2949.09   159.2 2948.58   168.3 2948.89   172.8 2948.72   179.7 2947.59
   194.5 2946.86   202.12947.618   213.5 2949.27   254.2 2951.27   268.5 2951.23
   272.3 2951.78   277.4 2953.85   281.4 2956.69   285.9 2960.74   290.4 2963.66
   295.1 2964.22   299.5 2964.23     304 2965.31   312.9 2973.99   319.6    2977
#Mann= 3 ,-1,0
       0      .1       0   179.7    .045       0   202.1      .1       0
Bank Sta=179.7,202.1
XS Rating Curve= 0 ,0
Exp/Cntr(USF)=0,0
Exp/Cntr=0.3,0.1

Type RM Length L Ch R = 1 ,6001    ,170.7,166.9,166.3
XS GIS Cut Line= 2
2311555.79910307576663.3787533082311392.64816869 576952.73006201
#Sta/Elev= 30
       0 2975.22     2.1 2974.27    11.3 2968.54    15.5 2966.28    21.6 2965.52
      25 2964.57    48.1 2952.61    65.6 2945.68    70.9 2945.47    84.7  2945.8
    93.9 2945.26   124.4 2945.89   135.2 2945.46   168.4 2946.39   181.2 2946.02
   191.9 2944.54   200.7 2943.74     211 2944.62   227.1 2946.07     250 2945.01
   259.2  2945.8   263.8    2947   271.2 2950.46   285.9 2955.25   291.7 2956.53
     296 2956.87   300.6 2957.75   309.4 2959.83   318.9 2964.38   332.2 2964.27
#Mann= 4 ,-1,0
       0      .1       0   191.9    .045       0     211      .1       0
     260     .08       0
Bank Sta=191.9,211
XS Rating Curve= 0 ,0
Exp/Cntr(USF)=0,0
Exp/Cntr=0.3,0.1

Type RM Length L Ch R = 1 ,5835    ,199.2,197.7,195.9
XS GIS Cut Line= 2
2311435.85190044576604.826327382 2311270.9955556576887.924464383
#Sta/Elev= 30
       0 2978.65    17.6 2969.23    31.2 2963.37    46.7 2953.54    51.3 2951.51
      56 2949.88    60.6 2947.56    69.8 2943.86    81.9 2942.87    88.4 2940.82
    94.7 2940.14   106.9  2940.3   114.1 2940.88     130 2942.21   148.5 2942.06
     158 2942.42   172.6 2943.84   216.5 2943.54   227.2 2944.12   245.7 2943.34
   260.4 2944.68   272.1 2947.47   282.8 2948.27   292.6 2950.21   304.3 2954.35
   309.4 2956.67   315.2 2959.91   319.8 2963.52   324.4  2965.2   327.6 2965.41
#Mann= 3 ,-1,0
       0      .1       0    88.4    .045       0   114.1      .1       0
#XS Ineff= 2 , 0
                          177.07         2946.68
Permanent Ineff=
       F       F
Bank Sta=88.4,114.1
XS Rating Curve= 0 ,0
Exp/Cntr(USF)=0,0
Exp/Cntr=0.3,0.1

Type RM Length L Ch R = 1 ,5637    ,146.7,146.4,146.1
XS GIS Cut Line= 2
2311249.96215988576537.7468491362311118.07708401576829.372038457
#Sta/Elev= 30
       0 2972.68       7  2970.9    21.3 2965.72    38.9 2957.57    47.7  2954.1
    65.2 2942.48    67.4 2941.59    69.6  2940.8    87.2  2939.4    93.32938.198
   104.7  2937.7   110.82938.204   113.5 2938.56   126.7 2938.18   139.5 2940.86
   144.2 2941.09   159.7 2941.36   170.6 2940.77   192.5 2940.76   210.1 2942.11
   218.9 2941.37   236.7 2941.34   249.6 2940.62     254 2941.17   271.6 2949.28
   297.2 2958.91   306.2 2964.49   311.1 2966.66   315.3 2967.67   320.1 2967.82
#Mann= 3 ,-1,0
       0      .1       0    93.3    .045       0   110.8      .1       0
#XS Ineff= 1 ,-1
  159.52320.0608 2943.69
Permanent Ineff=
       F
Bank Sta=93.3,110.8
XS Rating Curve= 0 ,0
Exp/Cntr(USF)=0,0
Exp/Cntr=0.3,0.1

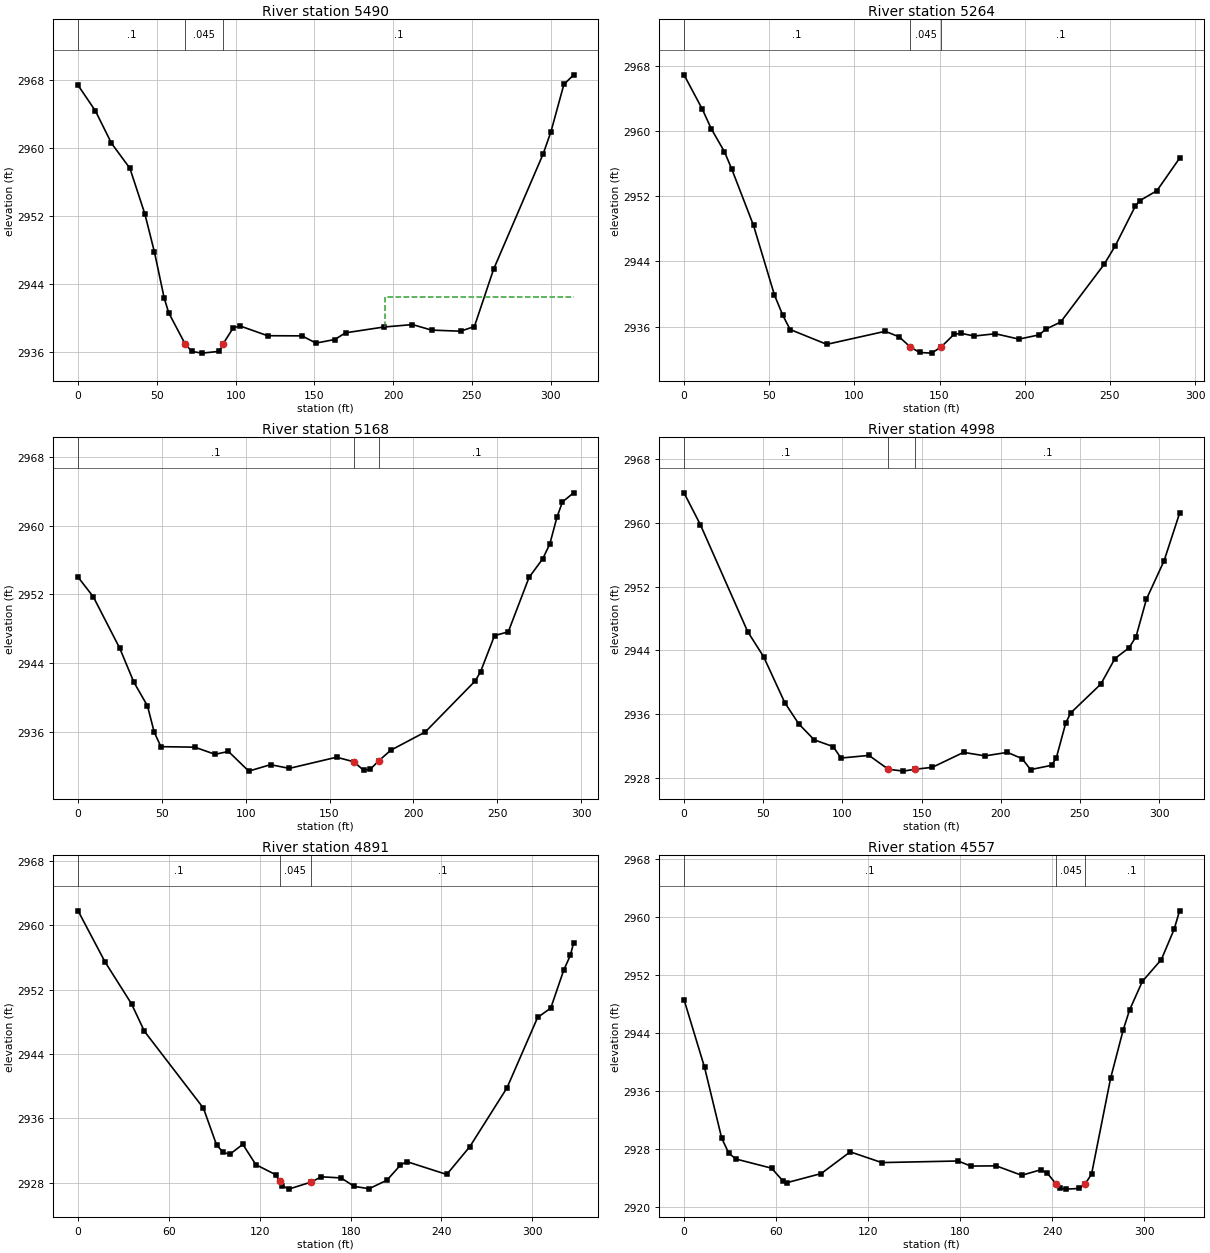
Type RM Length L Ch R = 1 ,5490    ,234.5,226.4,219.7
XS GIS Cut Line= 2
2311110.11850185576491.1322964572310982.78118721576778.778194696
#Sta/Elev= 30
       0 2967.38      11 2964.37    21.2 2960.56    32.9 2957.61    42.4 2952.24
    48.5 2947.74    54.7 2942.32    57.6 2940.58    67.9 2936.96    72.2 2936.06
    78.7 2935.86    89.7 2936.07    92.22936.984    98.5 2938.84   102.8 2939.06
   120.3 2937.91   142.2 2937.89     151 2937.04   162.9 2937.46   169.8 2938.25
     194 2938.93   212.3 2939.22   224.4 2938.57   242.8 2938.44   251.6 2938.99
   263.8 2945.74   295.3 2959.33   300.2 2961.92   308.4 2967.48   314.6 2968.61
#Mann= 3 ,-1,0
       0      .1       0    67.9    .045       0    92.2      .1       0
#XS Ineff= 1 ,-1
  195.01314.5711 2942.52
Permanent Ineff=
       F
Bank Sta=67.9,92.2
XS Rating Curve= 0 ,0
Exp/Cntr(USF)=0,0
Exp/Cntr=0.3,0.1

Type RM Length L Ch R = 1 ,5264    ,97.7,95.9,95.1
XS GIS Cut Line= 4
 2310898.9065013576403.1342472482310855.00918703 576515.84281193
2310850.89611134576570.7181181042310813.37708113576679.295917637
#Sta/Elev= 30
       0 2966.92    10.8 2962.68      16 2960.29    23.7 2957.49      28 2955.36
    40.8 2948.42    53.1 2939.87      58 2937.38    62.3 2935.64    83.8 2933.82
   118.1 2935.42   126.3 2934.74   132.92933.483   138.3 2932.82   145.3 2932.74
   150.92933.489   158.4 2935.03   162.4 2935.18   170.4 2934.84   182.8 2935.12
   196.6 2934.46   208.4 2934.98   212.4 2935.68   221.1 2936.56   246.7 2943.67
   253.2 2945.94     265 2950.83   267.5 2951.46   277.6 2952.69   290.9 2956.68
#Mann= 3 ,-1,0
       0      .1       0   132.9    .045       0   150.9      .1       0
Bank Sta=132.9,150.9
XS Rating Curve= 0 ,0
Exp/Cntr(USF)=0,0
Exp/Cntr=0.3,0.1

Type RM Length L Ch R = 1 ,5168    ,155.4,170.2,175.5
XS GIS Cut Line= 4
2310778.82097188576388.098113826 2310759.4171888576549.514071721
2310761.59963642576568.6841845262310733.92026551576678.947465509
#Sta/Elev= 30
       0 2954.02     9.1 2951.73    24.9 2945.72    33.3 2941.78    41.4 2939.03
    45.4 2935.98    49.4 2934.28    69.6 2934.22    81.7 2933.39    89.7 2933.72
   101.8 2931.43   114.8 2932.18     126 2931.75   154.2 2933.05   164.52932.519
   170.3 2931.53   174.3 2931.65   179.5 2932.66   186.5 2933.86   207.1 2935.99
     237 2941.96   240.1 2943.02   248.4 2947.21   256.6 2947.65     269 2953.99
   277.2 2956.17   281.4 2957.89   285.6 2960.97   288.9 2962.78   295.6 2963.84
#Mann= 3 ,-1,0
       0      .1       0   164.5    .045       0   179.5      .1       0
Bank Sta=164.5,179.5
XS Rating Curve= 0 ,0
Exp/Cntr(USF)=0,0
Exp/Cntr=0.3,0.1

Type RM Length L Ch R = 1 ,4998    ,105,107.2,102.6
XS GIS Cut Line= 2
2310720.51706958576343.8675672572310585.14479069576626.004841585
#Sta/Elev= 30
       0 2963.75    10.3 2959.77    40.2 2946.36    50.3  2943.2    63.6 2937.47
    72.4 2934.81    82.2  2932.8    94.2 2931.95    99.1 2930.52   116.8 2930.85
  128.92 2929.12   138.5 2928.88   145.82929.115   156.7 2929.35   176.5 2931.23
   190.1 2930.79   204.2 2931.23   213.5 2930.44   218.8 2929.07   232.1 2929.61
   235.1 2930.56     241  2934.9   244.1 2936.16   263.2 2939.79   272.1 2942.99
     281 2944.33   285.4 2945.73     292 2950.44   303.1 2955.23   312.9 2961.19
#Mann= 3 ,-1,0
       0      .1       0  128.92    .045       0   145.8      .1       0
Bank Sta=128.92,145.8
XS Rating Curve= 0 ,0
Exp/Cntr(USF)=0,0
Exp/Cntr=0.3,0.1

Type RM Length L Ch R = 1 ,4891    ,332.9,334,327.3
XS GIS Cut Line= 3
2310621.80263903576296.7155035772310559.27092202576447.360094551
2310496.73920501576599.141625835
#Sta/Elev= 30
       0 2961.77    17.8 2955.43    35.3 2950.22    43.8 2946.82    82.8 2937.27
    91.5 2932.69    95.8 2931.81   100.1 2931.53   108.8 2932.78   117.4 2930.26
   130.4 2929.02   133.2 2928.18   134.8 2927.66   139.1 2927.22   153.82928.089
   160.7 2928.75   173.7 2928.61   182.4 2927.56   192.2 2927.27     204 2928.33
   212.8 2930.18     217 2930.64   243.5 2929.04   258.8 2932.51   283.3  2939.8
   303.5 2948.53   312.2  2949.7   320.8 2954.43   325.1 2956.23   327.3 2957.82
#Mann= 3 ,-1,0
       0      .1       0   133.2    .045       0   153.8      .1       0
Bank Sta=133.2,153.8
XS Rating Curve= 0 ,0
Exp/Cntr(USF)=0,0
Exp/Cntr=0.3,0.1

Type RM Length L Ch R = 1 ,4557    ,245.9,242.6,233.9
XS GIS Cut Line= 3
2310370.94848177576259.9116617132310315.14866175576355.254063087
2310259.67504966576560.624306256
#Sta/Elev= 30
       0 2948.62    13.4 2939.27    24.6 2929.49    29.2 2927.44    33.9 2926.63
    57.1 2925.37    64.3 2923.66    67.3 2923.38    89.5 2924.63   108.4 2927.62
     129 2926.14   178.8 2926.36     187 2925.66   203.6 2925.69   220.2 2924.39
   232.6 2925.14   236.8 2924.71   242.92923.132   245.1 2922.59   249.2 2922.48
   257.5 2922.57   261.42923.119   265.8 2924.56   278.2 2937.76   286.5 2944.49
   290.6 2947.19   298.9 2951.12   311.3 2954.14   319.6 2958.29   323.2 2960.86
#Mann= 3 ,-1,0
       0      .1       0   242.9    .045       0   261.4      .1       0
Bank Sta=242.9,261.4
XS Rating Curve= 0 ,0
Exp/Cntr(USF)=0,0
Exp/Cntr=0.3,0.1