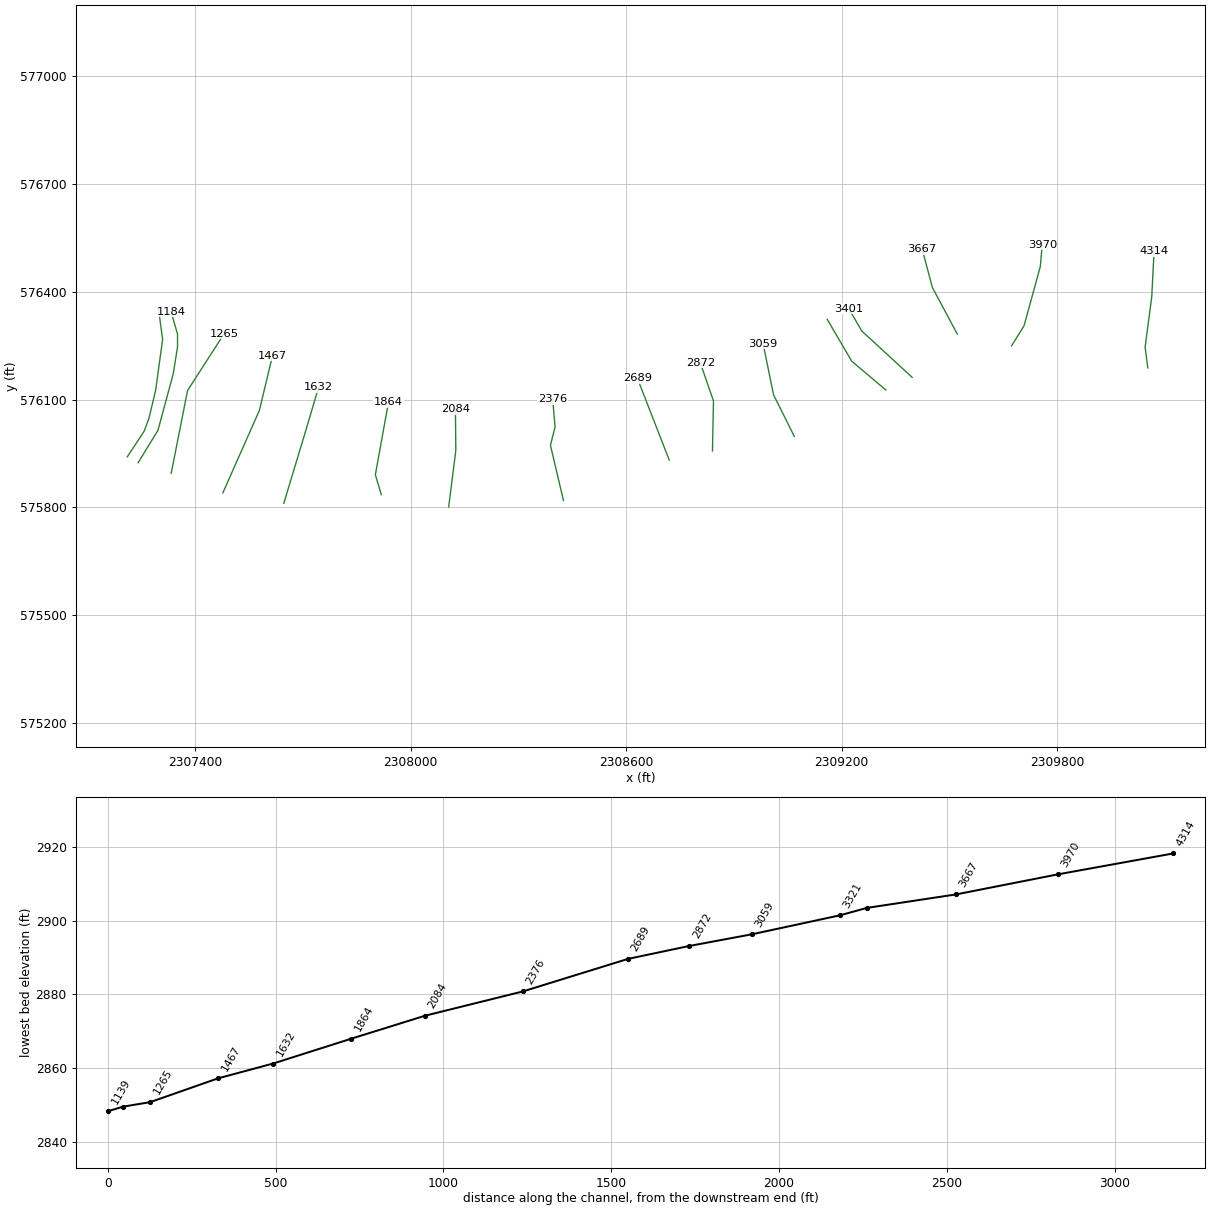
HEC-RAS study MNTNLCKCKT1.prj: MNTNLCKCKT1

--- MNTNLCKCKT1.g01 (geometry) --- (continued)

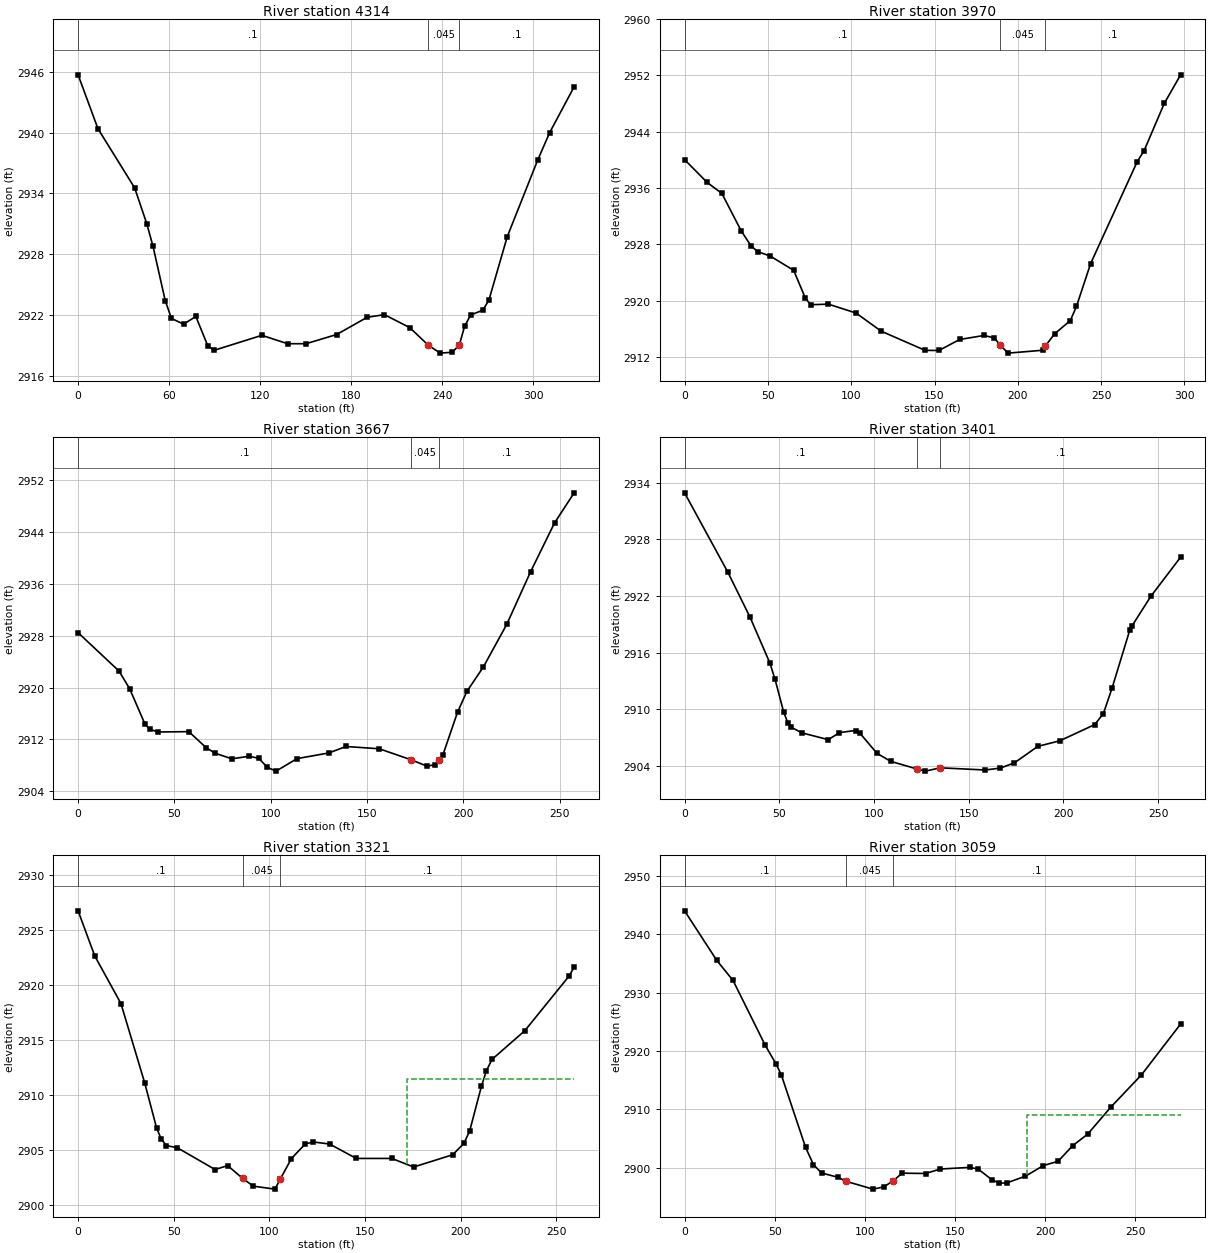
Type RM Length L Ch R = 1 ,4314    ,347,344.5,335.4
XS GIS Cut Line= 4
2310052.26475834576188.2037885322310044.89300058576246.507690828
2310063.30154596576385.7202708722310069.81811889576513.302632488
#Sta/Elev= 30
       0 2945.72    13.1 2940.39    37.3 2934.54    45.3 2930.99    49.4 2928.76
    57.4 2923.42    61.5 2921.65    69.5 2921.08    77.6 2921.84    85.5 2918.93
    89.7  2918.5   121.1 2919.98   138.1 2919.15   150.2 2919.15   170.4 2920.06
   190.6 2921.77   201.9 2922.02   218.6 2920.74   230.7 2919.01   238.7 2918.22
   246.7 2918.31   251.32919.053   254.7 2920.87   258.7 2921.99   266.7 2922.46
   270.7 2923.45   282.8 2929.72   302.8 2937.27   310.8 2940.02   326.9 2944.54
#Mann= 3 ,-1,0
       0      .1       0   230.7    .045       0   251.3      .1       0
Bank Sta=230.7,251.3
XS Rating Curve= 0 ,0
Exp/Cntr(USF)=0,0
Exp/Cntr=0.3,0.1

Type RM Length L Ch R = 1 ,3970    ,292.3,302.9,313.5
XS GIS Cut Line= 4
2309673.02595096576249.532480743 2309707.7026304576305.242555896
2309753.18024277576470.6673708912309758.29647416576530.925207281
#Sta/Elev= 30
       0 2940.04    13.6 2936.79    22.4 2935.23      34 2929.91    39.8 2927.82
    43.8 2926.97    51.4 2926.34    65.5  2924.3    72.5 2920.35    75.7 2919.42
    86.3  2919.5   102.9 2918.24     118 2915.66   144.4 2912.93   152.7 2912.92
   165.1 2914.48   179.8 2915.05   185.9  2914.7   189.6 2913.63   194.2 2912.54
   214.9 2912.95   216.62913.571   222.1 2915.29   231.5 2917.16   235.2 2919.18
   243.7 2925.27   271.7 2939.77   275.8 2941.32   287.9 2948.03   297.7 2952.09
#Mann= 3 ,-1,0
       0      .1       0   189.6    .045       0   216.6      .1       0
Bank Sta=189.6,216.6
XS Rating Curve= 0 ,0
Exp/Cntr(USF)=0,0
Exp/Cntr=0.3,0.1

Type RM Length L Ch R = 1 ,3667    ,254.4,265.7,274.9
XS GIS Cut Line= 3
2309521.81288983576282.5037497112309452.45953097576412.114944965
2309424.03602324576518.987334034
#Sta/Elev= 30
       0 2928.47    21.2 2922.56    26.8 2919.81    34.8 2914.31    37.4 2913.54
    41.6 2913.15    57.5  2913.2    66.5 2910.73    71.1 2909.88    79.8 2909.01
    88.9  2909.4    93.8 2909.09    98.3 2907.69   102.8 2907.11   113.7 2909.04
   130.3 2909.92   139.1 2910.91   156.4 2910.56   172.9 2908.86   181.2 2907.88
   185.4 2908.11   187.3 2908.84   189.5 2909.66   197.1 2916.25   201.9 2919.41
   210.4 2923.15   222.6 2929.75     235 2937.88   247.4 2945.39   257.6 2950.04
#Mann= 3 ,-1,0
       0      .1       0   172.9    .045       0   187.3      .1       0
Bank Sta=172.9,187.3
XS Rating Curve= 0 ,0
Exp/Cntr(USF)=0,0
Exp/Cntr=0.3,0.1

Type RM Length L Ch R = 1 ,3401    ,79.6,80.4,81
XS GIS Cut Line= 3
 2309396.3047718576161.7590462592309255.93958928576290.900117887
2309220.32336692 576352.46379118
#Sta/Elev= 30
       0 2932.91    22.8 2924.53    34.6 2919.73      45 2914.92    47.8 2913.15
    52.3 2909.72    54.5 2908.57    56.3 2908.09      62  2907.5    75.9 2906.78
    81.8 2907.53    90.3 2907.75    92.6 2907.46   101.6 2905.33   108.9 2904.48
   122.62903.686   127.1 2903.45     135  2903.8   158.7 2903.57   166.7 2903.77
   174.1 2904.32   186.5 2906.07   198.1 2906.66   216.5 2908.37   221.1 2909.53
   225.7 2912.23     235 2918.34   236.1 2918.78   246.2 2921.96   261.9  2926.1
#Mann= 3 ,-1,0
       0      .1       0   122.6    .045       0     135      .1       0
Bank Sta=122.6,135
XS Rating Curve= 0 ,0
Exp/Cntr(USF)=0,0
Exp/Cntr=0.3,0.1

Type RM Length L Ch R = 1 ,3321    ,267.6,262.1,252.3
XS GIS Cut Line= 3
2309322.84833572576126.742927345 2309227.9138199576206.897219147
2309159.69740134576323.433600844
#Sta/Elev= 30
       0 2926.74     8.7 2922.64    22.4 2918.31    34.8 2911.11      41 2907.02
    43.4 2906.01    46.2  2905.4    51.9  2905.2    71.6 2903.22    78.2 2903.58
      862902.418    91.6 2901.71   102.9 2901.44   105.8 2902.38   111.5 2904.22
   118.7 2905.54   122.8 2905.73   131.5 2905.54   145.4 2904.23     164 2904.23
   175.4 2903.45   195.9 2904.57   201.7 2905.61   204.7 2906.73   210.8 2910.77
   213.4 2912.19   216.4 2913.24   233.5 2915.84   256.7 2920.82   259.3 2921.63
#Mann= 3 ,-1,0
       0      .1       0      86    .045       0   105.8      .1       0
#XS Ineff= 1 ,-1
  171.93259.2809 2911.41
Permanent Ineff=
       F
Bank Sta=86,105.8
XS Rating Curve= 0 ,0
Exp/Cntr(USF)=0,0
Exp/Cntr=0.3,0.1

Type RM Length L Ch R = 1 ,3059    ,198.8,186.8,176.4
XS GIS Cut Line= 3
2309068.17370645575997.1317320912309010.18975068576113.668113789
2308981.19777279576255.785652444
#Sta/Elev= 30
       0 2944.05    17.9 2935.53    26.9  2932.1    44.8 2920.95    50.8 2917.76
    53.7 2915.88    67.1  2903.5    71.5  2900.5      76 2899.07    84.9 2898.35
    89.5 2897.65   104.5  2896.3   110.4 2896.67   115.7 2897.71   120.7 2899.04
   133.7 2898.98   141.9 2899.75   158.2 2900.03   162.9 2899.74   170.5 2897.91
   174.6 2897.33   178.7 2897.36   189.1 2898.52   199.1 2900.35   207.2 2901.07
   215.4 2903.78   223.6 2905.72   236.6 2910.41   253.5 2915.91   275.2 2924.63
#Mann= 3 ,-1,0
       0      .1       0    89.5    .045       0   115.7      .1       0
#XS Ineff= 2 , 0
                          189.87         2909.02
Permanent Ineff=
       F       F
Bank Sta=89.5,115.7
XS Rating Curve= 0 ,0
Exp/Cntr(USF)=0,0
Exp/Cntr=0.3,0.1

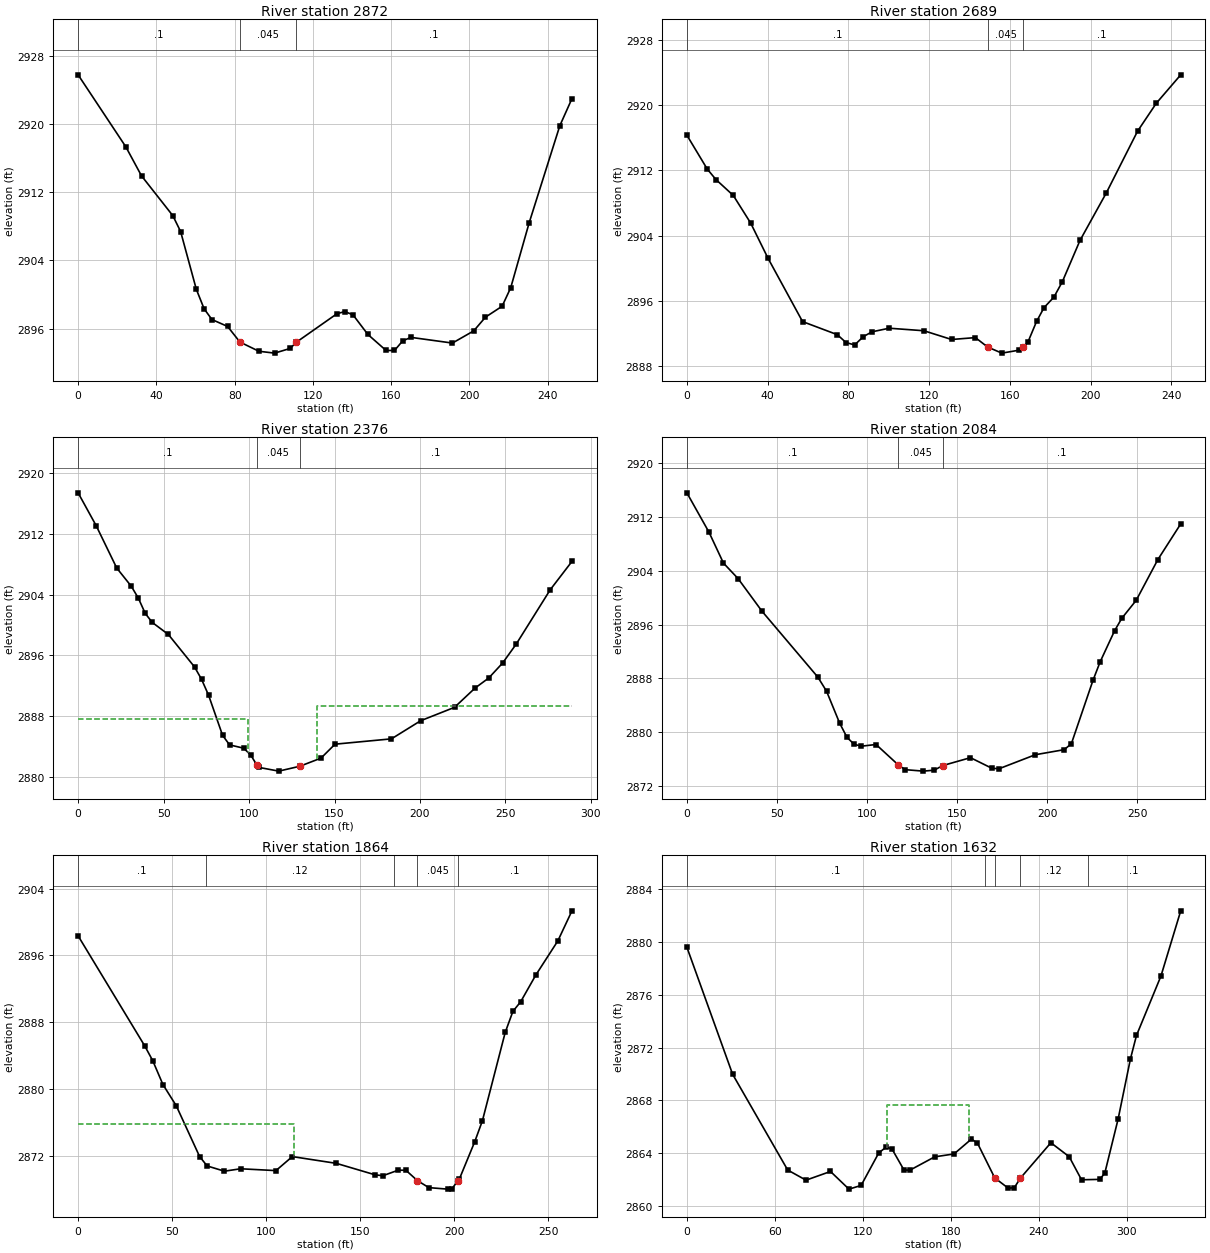
Type RM Length L Ch R = 1 ,2872    ,176.6,183,189.4
XS GIS Cut Line= 3
2308840.21717444575956.7703511132308843.05952522576096.045538996
2308806.10896517576202.917928064
#Sta/Elev= 30
       0 2925.78    24.4 2917.33    32.4 2913.93    48.4 2909.26    52.4 2907.39
    60.4 2900.63    64.4 2898.33    68.4 2897.07    76.4 2896.26    82.7 2894.43
    92.4 2893.35   100.4 2893.13   108.4 2893.68   111.42894.385   132.4 2897.77
   136.4    2898   140.5 2897.62   148.1 2895.32   157.4 2893.44   161.7 2893.44
   165.9 2894.57   170.1 2894.98   191.3 2894.31   202.2 2895.74   208.2 2897.35
   216.7 2898.63   221.1  2900.8   230.5  2908.4   246.2 2919.81   252.4 2922.99
#Mann= 3 ,-1,0
       0      .1       0    82.7    .045       0   111.4      .1       0
Bank Sta=82.7,111.4
XS Rating Curve= 0 ,0
Exp/Cntr(USF)=0,0
Exp/Cntr=0.3,0.1

Type RM Length L Ch R = 1 ,2689    ,315,312.7,306.6
XS GIS Cut Line= 2
2308719.70150167 575931.757664312308631.02015754576159.714196313
#Sta/Elev= 30
       0  2916.3    10.1 2912.15    14.4 2910.87      23 2908.92    31.6 2905.54
    40.2 2901.23    57.3 2893.48    74.5 2891.88    78.8 2890.92    83.1 2890.62
    87.4 2891.64    91.7 2892.23   100.2 2892.67   117.4 2892.36   131.1 2891.29
   142.9 2891.52     149 2890.36     156 2889.62   164.5 2889.98   166.7 2890.37
   168.9 2890.96   173.2  2893.5   176.9 2895.19   181.8 2896.48     186 2898.38
   194.7 2903.41   207.8 2909.26   223.2 2916.78   232.5 2920.21   244.6 2923.69
#Mann= 3 ,-1,0
       0      .1       0     149    .045       0   166.7      .1       0
Bank Sta=149,166.7
XS Rating Curve= 0 ,0
Exp/Cntr(USF)=0,0
Exp/Cntr=0.3,0.1

Type RM Length L Ch R = 1 ,2376    ,298.3,292.1,282.2
XS GIS Cut Line= 4
2308425.36520954575818.8989278262308389.08449271575972.683805429
 2308402.0696803576023.7136215252308395.20456144576101.662452383
#Sta/Elev= 30
       0 2917.37    10.6 2913.04    22.6 2907.49    31.1  2905.1    35.2 2903.55
    39.3 2901.52    43.4 2900.34    52.8 2898.76    68.1  2894.5    72.2 2892.88
    76.3  2890.8    84.5 2885.52    88.6 2884.26    96.9 2883.82     101 2882.92
   104.52881.633     106 2881.29   117.4 2880.81   129.7 2881.45   142.1 2882.52
   150.3 2884.35   183.3 2885.05   200.4 2887.43   220.2 2889.19   232.2 2891.72
   240.2 2893.04   248.3    2895   256.3  2897.5   276.2 2904.64   288.9 2908.36
#Mann= 3 ,-1,0
       0      .1       0   104.5    .045       0   129.7      .1       0
#XS Ineff= 2 , 0
           99.67 2887.71  140.03         2889.37
Permanent Ineff=
       F       F
Bank Sta=104.5,129.7
XS Rating Curve= 0 ,0
Exp/Cntr(USF)=0,0
Exp/Cntr=0.3,0.1

Type RM Length L Ch R = 1 ,2084    ,221.5,219.8,218.4
XS GIS Cut Line= 3
2308105.75373467575801.0095287472308125.65019009575958.475761577
2308124.51324978576073.875202966
#Sta/Elev= 30
       0  2915.6    12.3 2909.73    20.3 2905.15    28.4 2902.85    41.7 2897.99
    72.7 2888.19    77.5 2886.11    84.8 2881.34    88.9 2879.22    92.9 2878.19
    96.9 2877.92     105 2878.17   117.4 2875.12   121.1 2874.43   131.2 2874.21
   137.3 2874.35   141.9 2875.03   157.4 2876.21   169.4 2874.62   173.4 2874.58
   193.4 2876.65   209.4  2877.4   213.4 2878.28   225.4 2887.71   229.4 2890.48
   237.4 2895.09   241.4 2896.94   249.4 2899.62   261.4 2905.67   274.1 2910.98
#Mann= 3 ,-1,0
       0      .1       0   117.4    .045       0   141.9      .1       0
Bank Sta=117.4,141.9
XS Rating Curve= 0 ,0
Exp/Cntr(USF)=0,0
Exp/Cntr=0.3,0.1

Type RM Length L Ch R = 1 ,1864    ,231,232.4,227.7
XS GIS Cut Line= 3
2307918.15858365575835.1177380252307901.67294917575890.827813177
2307938.05503906576092.066247913
#Sta/Elev= 30
       0 2898.34    35.5 2885.12    39.7 2883.37    45.1 2880.52    52.2 2877.97
    64.6 2871.89    68.6 2870.76    77.8 2870.13    86.4 2870.42   105.2  2870.2
   113.9 2871.88   137.3 2871.07     158 2869.69   162.1 2869.59   170.2 2870.25
   174.3 2870.24   180.42869.005   186.5 2868.16   196.5 2867.98   198.7 2867.98
   201.8 2868.96   202.8 2869.23   210.9 2873.66     215 2876.19   227.1 2886.76
   231.2 2889.29   235.3 2890.43   243.4 2893.65   255.1 2897.74   262.6 2901.34
#Mann= 5 ,-1,0
       0      .1       0    68.1     .12       0   168.1      .1       0
   180.4    .045       0   201.8      .1       0
#XS Ineff= 2 , 0
          114.93  2875.8
Permanent Ineff=
       F       F
Bank Sta=180.4,201.8
XS Rating Curve= 0 ,0
Exp/Cntr(USF)=0,0
Exp/Cntr=0.3,0.1

Type RM Length L Ch R = 1 ,1632    ,161.6,164.9,168
XS GIS Cut Line= 3
2307646.75605766575811.3214010642307702.70839505575996.563261937
2307743.63824618576134.133039355
#Sta/Elev= 30
       0 2879.62    31.2 2869.98    68.8 2862.71    81.3 2861.94      98  2862.6
   110.6 2861.26   118.9 2861.54     131 2864.02   135.7 2864.42   139.8 2864.34
   148.2  2862.7   152.4 2862.71   169.1 2863.71   182.3 2863.93   194.2 2865.06
   198.3 2864.75   210.1 2862.11   219.2 2861.34   223.4 2861.36   227.62862.095
   248.4 2864.78   260.9 2863.72   269.3 2861.97   281.8    2862   285.2 2862.48
   294.3 2866.59   302.7 2871.15   306.8 2872.92   323.5 2877.43     337 2882.38
#Mann= 5 ,-1,0
       0      .1       0  203.51     .12       0   210.1    .045       0
   227.6     .12       0  273.51      .1       0
#XS Ineff= 1 ,-1
  136.63  192.44 2867.63
Permanent Ineff=
       F
Bank Sta=210.1,227.6
XS Rating Curve= 0 ,0
Exp/Cntr(USF)=0,0
Exp/Cntr=0.3,0.1

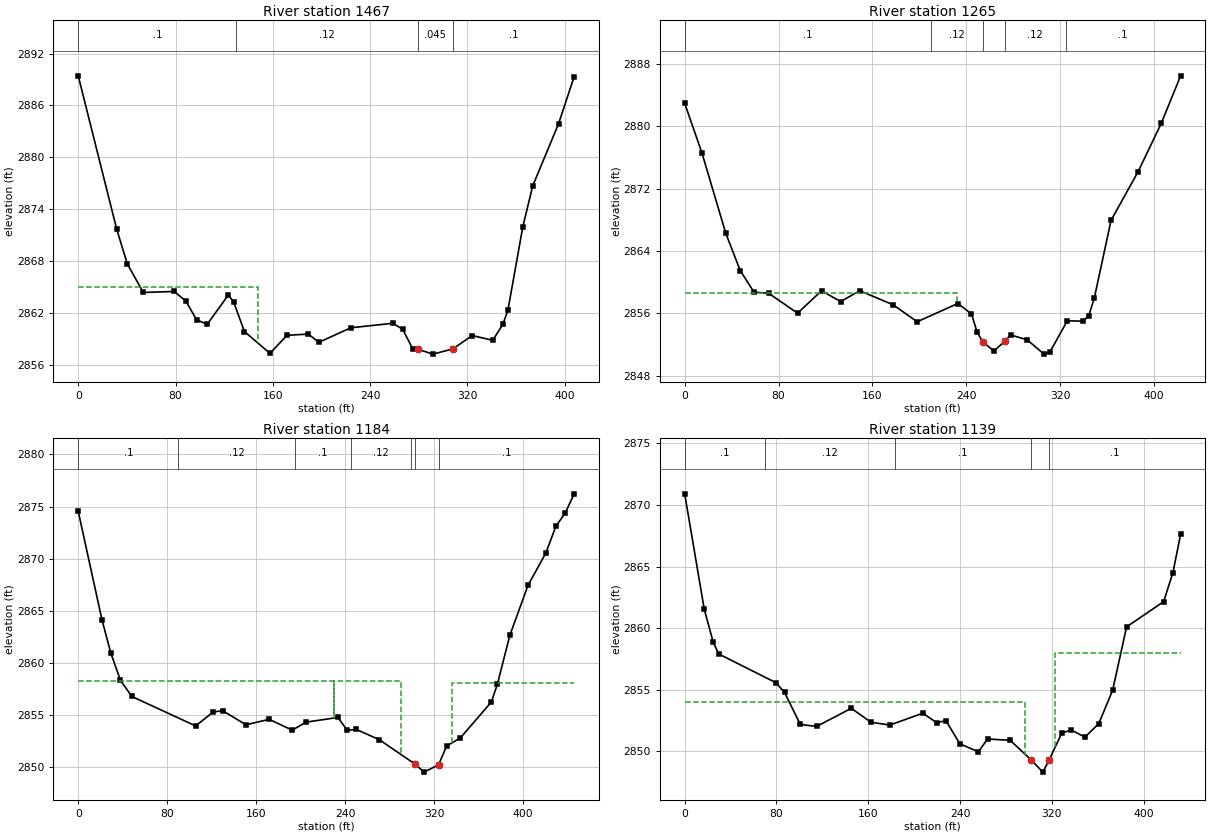
Type RM Length L Ch R = 1 ,1467    ,208.7,201.6,196.5
XS GIS Cut Line= 3
2307477.02574366575840.2339694162307578.78190134576069.895911883
2307615.16399124576222.245913322
#Sta/Elev= 30
       0 2889.43    31.7 2871.65    40.4 2867.65    53.5 2864.36    78.9 2864.47
    88.5 2863.36    97.3  2861.2     106 2860.66   123.5 2864.07   127.9 2863.22
   136.7 2859.83   157.7 2857.31   171.7  2859.4   189.2 2859.54   197.9 2858.59
   224.2 2860.27   258.7 2860.79   266.9 2860.08     275 2857.84   279.2 2857.79
   291.6 2857.22     308 2857.82     324 2859.37   340.9 2858.82   349.2 2860.68
   353.3 2862.28   365.6 2871.97   373.8 2876.72     395 2883.89   407.8 2889.33
#Mann= 4 ,-1,0
       0      .1       0     130     .12       0   279.2    .045       0
     308      .1       0
#XS Ineff= 2 , 0
          147.84 2864.99
Permanent Ineff=
       F       F
Bank Sta=279.2,308
XS Rating Curve= 0 ,0
Exp/Cntr(USF)=0,0
Exp/Cntr=0.3,0.1

Type RM Length L Ch R = 1 ,1265    ,73.7,81.3,91.2
BEGIN DESCRIPTION:
xs 4
END DESCRIPTION:
XS GIS Cut Line= 3
2307333.20279454 575894.807104262307378.68040691576125.037516882
2307480.43656459576283.072219866
#Sta/Elev= 30
       0 2882.95    14.8 2876.54      35 2866.29    47.3 2861.51      59 2858.75
    71.7 2858.58    96.2 2856.04   116.6 2858.91   132.9 2857.53   149.2 2858.92
   177.7 2857.11   198.1 2854.94   232.7 2857.28   244.4 2855.95   249.1 2853.64
   253.9 2852.39   263.4 2851.19   272.9 2852.44   277.7 2853.25   291.9 2852.62
   306.2 2850.79   311.3 2851.09   326.1 2855.07   339.5 2855.01   344.3 2855.73
     349 2857.94   363.3 2867.93   386.4 2874.19   406.1 2880.38   422.6 2886.47
#Mann= 5 ,-1,0
       0      .1       0     210     .12       0   253.9    .045       0
   272.9     .12       0  324.68      .1       0
#XS Ineff= 2 , 0
          231.88 2858.57
Permanent Ineff=
       F       F
Bank Sta=253.9,272.9
XS Rating Curve= 0 ,0
Exp/Cntr(USF)=0,0
Exp/Cntr=0.5,0.3

Type RM Length L Ch R = 1 ,1184    ,45.5,44.8,44.3
BEGIN DESCRIPTION:
xs 3
END DESCRIPTION:
XS GIS Cut Line= 6
2307241.03636845575924.0646521152307296.25223449 576014.18583673
2307338.88749609576171.6520695612307350.82536934576246.690129971
2307350.82536934576281.9352795572307332.63432439 576345.03546672
#Sta/Elev= 30
       0 2874.55    21.3 2864.17    29.3 2860.96      38 2858.34    48.2  2856.8
   105.5 2853.98   121.4 2855.31   129.8 2855.44   150.8 2854.09   171.7 2854.61
   192.4 2853.57   204.8 2854.34   233.5 2854.79   241.7 2853.56     250 2853.64
   270.5 2852.67   302.9 2850.31   302.9  2850.3     311 2849.55   323.92850.253
   331.2 2852.06   343.4 2852.81   371.4 2856.28   376.8 2857.98     388 2862.66
   404.4 2867.47   420.4 2870.56   429.4 2873.12   437.7 2874.36   445.8 2876.22
#Mann= 7 ,-1,0
       0      .1       0      90     .12       0  194.91      .1       0
  244.91     .12       0  298.95      .1       0   302.9    .045       0
   323.9      .1       0
#XS Ineff= 3 ,-1
       0     230 2858.28     230     2902858.283     336   445.8 2858.13
Permanent Ineff=
       F       F       F
Bank Sta=302.9,323.9
XS Rating Curve= 0 ,0
Exp/Cntr(USF)=0,0
Exp/Cntr=0.5,0.3

Type RM Length L Ch R = 1 ,1139    ,117.4,116.5,114
BEGIN DESCRIPTION:
xs 2
END DESCRIPTION:
XS GIS Cut Line= 6
2307210.82307474575940.4161374552307257.84200438576011.782864209
2307271.01363686576046.9957408212307289.90224387576125.916273387
 2307309.2625021576267.2643178692307297.95764496576351.857108576
#Sta/Elev= 30
       0 2870.91      17 2861.57    24.9 2858.85    29.7 2857.91    79.5 2855.58
      87 2854.79   100.8 2852.19     115 2852.03   145.2  2853.5   162.3 2852.37
   178.8 2852.14   207.5  2853.1   219.6 2852.34   227.7 2852.49   239.8 2850.62
   255.9 2849.97     264 2851.01   283.7  2850.9   302.1  2849.3   312.1 2848.32
   317.6  2849.3   328.6 2851.48   336.7 2851.75   348.8 2851.16   360.9 2852.26
     373 2854.98   385.1 2860.11   417.4 2862.16   425.5 2864.52   432.2 2867.63
#Mann= 5 ,-1,0
       0      .1       0      70     .12       0  183.06      .1       0
   302.1    .045       0   317.6      .1       0
#XS Ineff= 2 , 0
             297    2854     323            2858
Permanent Ineff=
       F       F
Bank Sta=302.1,317.6
XS Rating Curve= 0 ,0
Exp/Cntr(USF)=0,0
Exp/Cntr=0.5,0.3