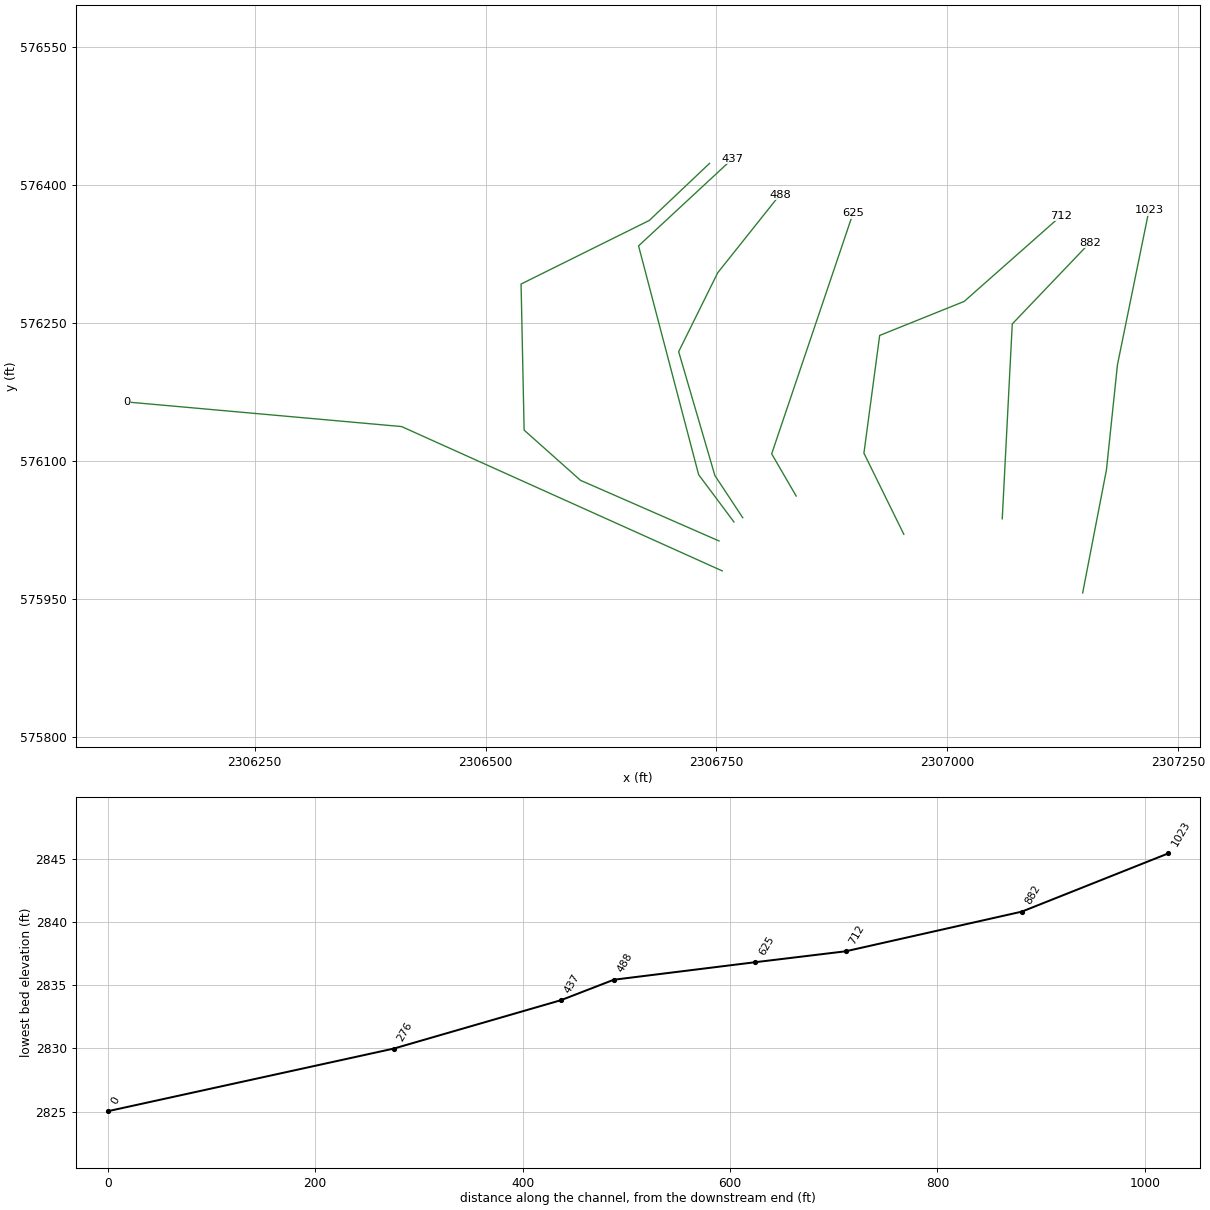
HEC-RAS study MNTNLCKCKT1.prj: MNTNLCKCKT1

--- MNTNLCKCKT1.g01 (geometry) --- (continued)

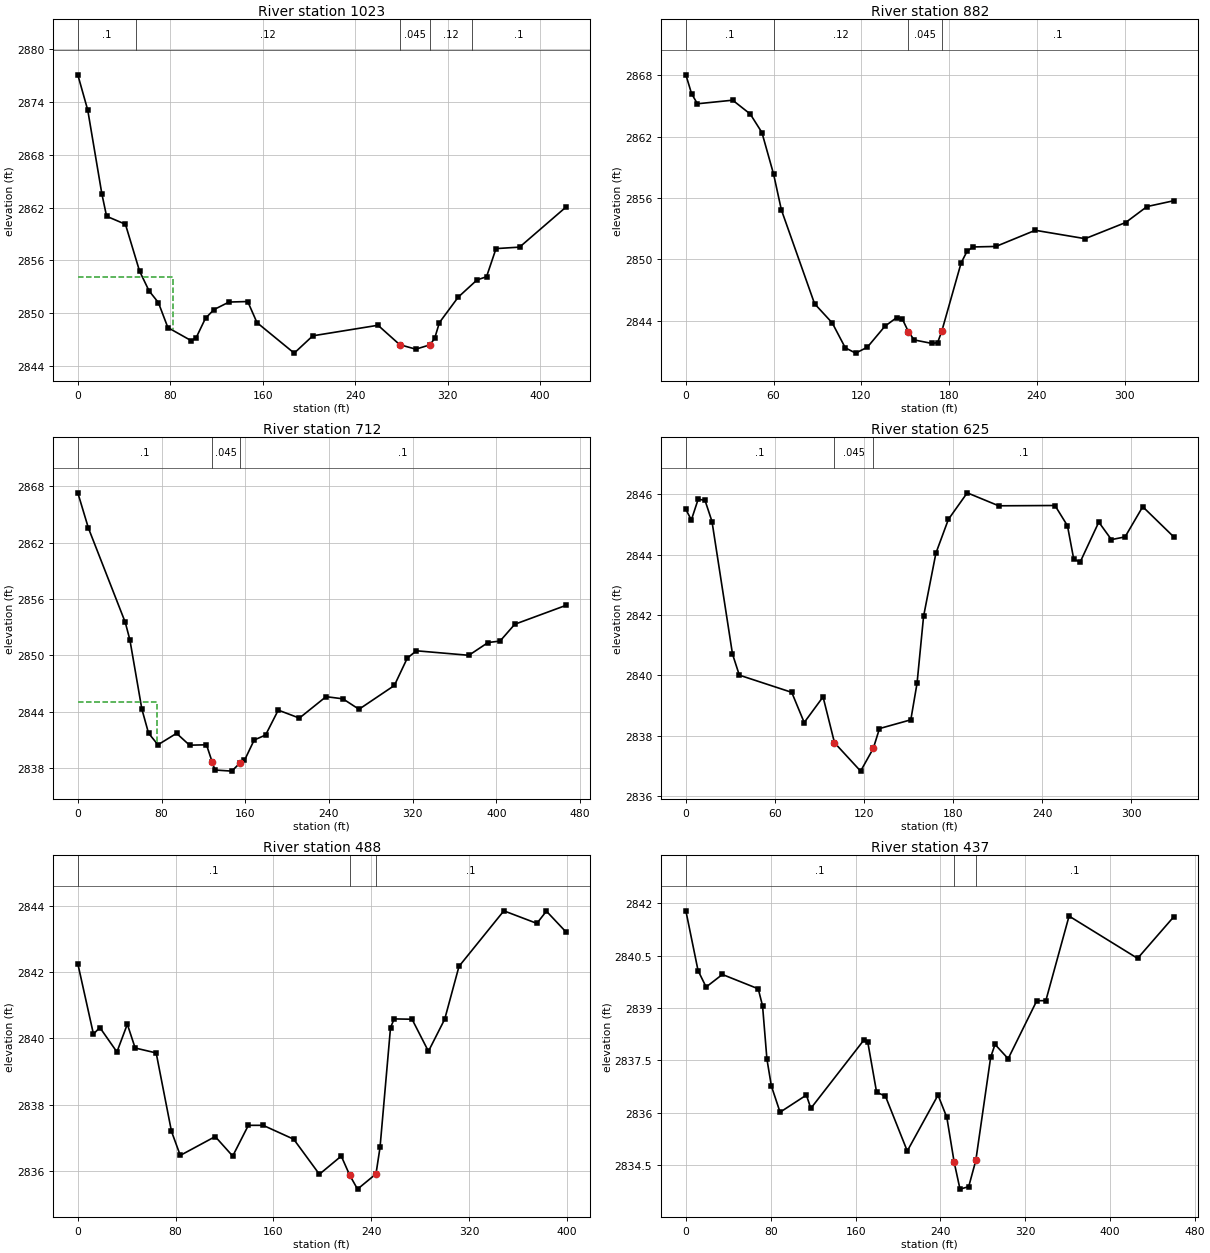
Type RM Length L Ch R = 1 ,1023    ,139.9,141.2,148.2
BEGIN DESCRIPTION:
xs 1
END DESCRIPTION:
XS GIS Cut Line= 4
2307146.58668614575956.7138058192307172.32574079 576090.36083745
2307184.26361403576204.6233385292307218.37182331576372.322034142
#Sta/Elev= 30
       0  2877.1     8.6 2873.08    20.8 2863.56    24.9 2861.01    41.2  2860.1
    53.4 2854.78    61.6 2852.53    69.7 2851.19    77.9 2848.35    98.2 2846.85
   102.3 2847.17   110.5 2849.42   117.9  2850.4   130.8 2851.25     147 2851.31
     155 2848.91   187.2 2845.44   203.3 2847.41   259.7 2848.61   278.5  2846.4
   292.4 2845.89   304.6 2846.38   308.7 2847.11   312.8 2848.91   329.1 2851.81
   345.4 2853.77   353.6 2854.13   361.8 2857.33   382.2  2857.5   422.1 2862.03
#Mann= 5 ,-1,0
       0      .1       0      50     .12       0   278.5    .045       0
   304.6     .12       0  340.99      .1       0
#XS Ineff= 2 , 0
           82.23 2854.05
Permanent Ineff=
       F       F
Bank Sta=278.5,304.6
XS Rating Curve= 0 ,0
Exp/Cntr(USF)=0,0
Exp/Cntr=0.3,0.1

Type RM Length L Ch R = 1 ,882     ,169.2,169.9,164.2
XS GIS Cut Line= 3
2307059.49263939576037.255701702 2307070.3492281576248.959181418
2307154.18621864576337.018178679
#Sta/Elev= 30
       0 2868.04     3.9  2866.2     7.9 2865.21      32 2865.56      44 2864.21
      52  2862.4      60 2858.32    65.3 2854.84      88 2845.66   100.1 2843.78
     109 2841.35   116.1 2840.83   124.1 2841.41   136.1 2843.46   144.1  2844.3
   148.1 2844.14   152.1 2842.94   156.1 2842.12   168.2 2841.78   172.1 2841.85
  174.93 2842.95   188.2 2849.65   192.2 2850.77   196.2 2851.21     212 2851.26
   238.9 2852.84     273 2852.02   300.7  2853.6   315.3 2855.16   333.6 2855.73
#Mann= 4 ,-1,0
       0      .1       0      60     .12       0   152.1    .045       0
  174.93      .1       0
Bank Sta=152.1,174.93
XS Rating Curve= 0 ,0
Exp/Cntr(USF)=0,0
Exp/Cntr=0.3,0.1

Type RM Length L Ch R = 1 ,712     ,91.9,86.9,83
XS GIS Cut Line= 5
 2306952.8962611576020.4390084322306909.69252935576108.551882398
2306926.74663399576236.4576671882307018.27032888576273.408227238
2307123.43730749576366.637332596
#Sta/Elev= 30
       0 2867.29    10.1 2863.55    45.4  2853.5    49.8 2851.64    61.2  2844.3
    67.6 2841.73    76.6 2840.49    94.4 2841.71   106.8 2840.45     123 2840.49
   128.6 2838.61   131.1 2837.81   147.2 2837.69   155.3 2838.59   159.3 2838.83
   168.6    2841   179.5 2841.53   191.6 2844.18   211.8 2843.33   237.3 2845.61
   253.4 2845.38   268.8 2844.27   302.6  2846.8   314.9  2849.7   323.6 2850.49
   373.8 2850.01   392.2 2851.37   403.6 2851.52   417.7 2853.31   466.4 2855.31
#Mann= 3 ,-1,0
       0      .1       0   128.6    .045       0   155.3      .1       0
#XS Ineff= 2 , 0
           75.58 2845.07
Permanent Ineff=
       F       F
Bank Sta=128.6,155.3
XS Rating Curve= 0 ,0
Exp/Cntr(USF)=0,0
Exp/Cntr=0.3,0.1

Type RM Length L Ch R = 1 ,625     ,141.9,136.6,134.6
XS GIS Cut Line= 3
2306836.32942716576061.9845981932306809.79109921576107.823528274
2306897.85009647576368.984800972
#Sta/Elev= 30
       0  2845.5     3.7 2845.15     8.3 2845.84    12.9  2845.8    17.6  2845.1
    31.4 2840.71      36 2840.01    71.3 2839.44    79.7 2838.44    92.4 2839.29
   100.1 2837.77   117.7 2836.83   126.2 2837.58   130.4 2838.24   151.5 2838.53
   155.7 2839.74   160.1 2841.96   168.4 2844.05   176.8 2845.17   189.5 2846.05
   210.7 2845.62   248.6 2845.63     257 2844.96   261.2 2843.86   265.5 2843.75
   278.1 2845.08   286.6  2844.5   295.8 2844.59   307.7 2845.59   328.6 2844.59
#Mann= 3 ,-1,0
       0      .1       0   100.1    .045       0   126.2      .1       0
Bank Sta=100.1,126.2
XS Rating Curve= 0 ,0
Exp/Cntr(USF)=0,0
Exp/Cntr=0.3,0.1

Type RM Length L Ch R = 1 ,488     ,39.3,51,67.3
XS GIS Cut Line= 5
2306778.42762074576038.4619893362306748.27042989576084.300919417
 2306709.0660818576218.8019905752306751.28614898576304.448412569
2306818.83825647576389.491690745
#Sta/Elev= 30
       0 2842.26    12.8 2840.13      18 2840.33      32 2839.59    40.5 2840.43
    46.9 2839.71    64.1 2839.56    76.6 2837.19    83.8 2836.46   112.4 2837.03
   126.7 2836.44   139.5 2837.37   151.6 2837.37   176.6 2836.95   197.6 2835.89
   215.5 2836.44   222.42835.863   228.8 2835.44   243.9  2835.9   247.2  2836.7
   255.8 2840.33   258.8 2840.59   273.4 2840.58   286.8 2839.61   300.1 2840.58
   311.8 2842.18   348.5 2843.86   375.5 2843.48   383.3 2843.85   399.1 2843.23
#Mann= 3 ,-1,0
       0      .1       0   222.4    .045       0   243.9      .1       0
Bank Sta=222.4,243.9
XS Rating Curve= 0 ,0
Exp/Cntr(USF)=0,0
Exp/Cntr=0.3,0.1

Type RM Length L Ch R = 1 ,437     ,166.3,161.2,156.8
XS GIS Cut Line= 4
2306768.93109621576033.8182157342306730.68885006576085.200036356
2306665.64903822 576333.74503159 2306767.3412141576428.383694124
#Sta/Elev= 30
       0 2841.78    11.5 2840.07    19.1  2839.6    34.4 2839.96    68.2 2839.55
    72.3 2839.06    76.4 2837.54    80.6 2836.77    88.8 2836.02   113.6 2836.51
   117.8 2836.13   167.7 2838.08   171.5 2838.02   179.8 2836.59   188.1 2836.48
   208.7 2834.91   237.7 2836.51     246 2835.87   252.9 2834.59   258.4 2833.82
   266.6 2833.89   273.3 2834.64   287.3 2837.59   291.4 2837.96   303.8 2837.55
   330.8 2839.21   339.3 2839.21   361.2 2841.63   425.8 2840.42   459.9 2841.61
#Mann= 3 ,-1,0
       0      .1       0   252.9    .045       0   273.3      .1       0
Bank Sta=252.9,273.3
XS Rating Curve= 0 ,0
Exp/Cntr=0.3,0.1

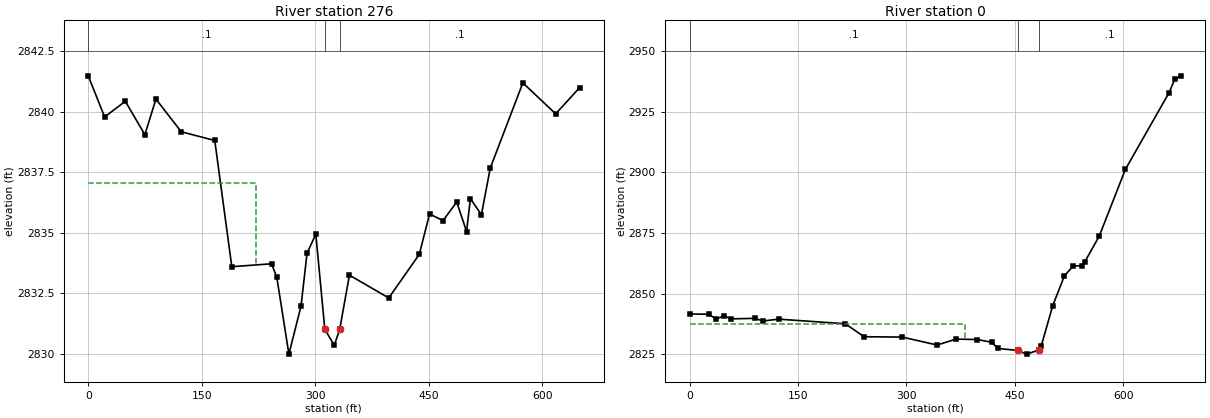
Type RM Length L Ch R = 1 ,276     ,72.9,275.8,69.8
XS GIS Cut Line= 6
2306752.75592907576013.1916732512306602.76019985576079.044337169
2306541.70976167576133.5971328842306538.39574611576292.296623006
2306677.25804007576361.3815522852306742.51265598 576423.37915265
#Sta/Elev= 30
       0 2841.48    21.7 2839.78      49 2840.43    74.9 2839.05    89.5 2840.52
     123 2839.17   167.3 2838.81   189.8  2833.6   242.4 2833.72   249.3 2833.16
   265.3 2829.99   281.3 2831.97   289.3 2834.16   300.9 2834.94  312.76 2831.02
   325.3 2830.35  332.44 2831.01   345.3 2833.25   397.3 2832.31   437.7 2834.11
   451.3 2835.78     469  2835.5   487.2 2836.27   500.2 2835.05   505.2 2836.41
   519.8 2835.75   531.5 2837.67   574.6 2841.19     618 2839.91   649.5 2840.99
#Mann= 3 ,0,0
       0      .1       0  312.76    .045       0  332.44      .1       0
#XS Ineff= 2 , 0
          222.09 2837.05
Permanent Ineff=
       F       F
Bank Sta=312.76,332.44
XS Rating Curve= 0 ,0
Exp/Cntr=0.3,0.1

Type RM Length L Ch R = 1 ,0       ,95.3,90.7,88.3
XS GIS Cut Line= 3
2306756.24020471575980.6717673332306408.97406651576137.464170868
 2306111.6492124 576164.17695073
#Sta/Elev= 30
       0 2841.62    26.4 2841.46    36.7 2839.56    48.3 2840.86    57.1 2839.57
    91.1 2839.79     101 2838.67     123 2839.46   215.2 2837.56   241.5 2832.21
   294.1 2832.06   342.4 2828.78   368.7 2831.23   397.9 2831.05     418 2829.92
   426.3 2827.37   454.1 2826.55   466.1 2825.03   483.7 2826.77   486.2 2828.18
   502.3 2845.03   518.4 2857.26   530.4 2861.34   542.5 2861.54   546.5 2863.02
   566.6 2873.68   602.8 2901.25     663 2932.74     671 2938.31   679.5 2939.81
#Mann= 3 ,-1,0
       0      .1       0   454.1    .045       0   483.7      .1       0
#XS Ineff= 2 , 0
          380.56 2837.64
Permanent Ineff=
       F       F
Bank Sta=454.1,483.7
XS Rating Curve= 0 ,0
Exp/Cntr=0.3,0.1
LCMann Table=0

Chan Stop Cuts=-1
Use User Specified Reach Order=0
Composite Channel Slope=5